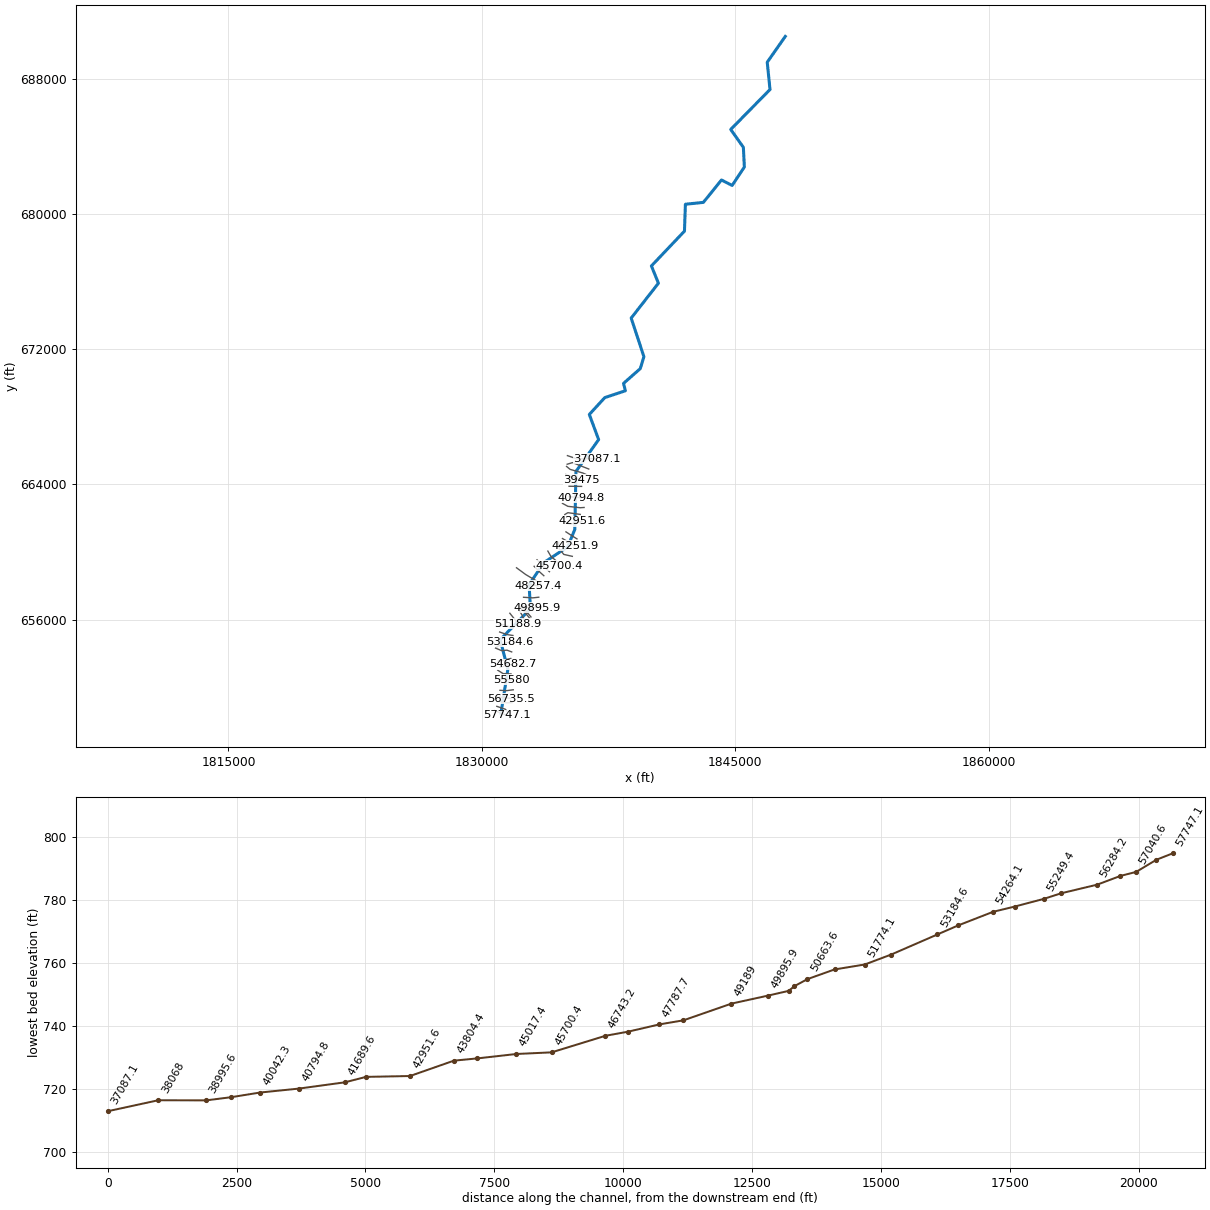
--- MFReedyCrk.prj (project) ---

Proj Title=MFReedyCrk
Current Plan=p01
Default Exp/Contr=0,0
English Units
Geom File=g01
Flow File=f01
Plan File=p01
BEGIN DESCRIPTION:
AMEC Environment & Infrastructure, 2013
Projection: NAD 1983 State Plane West Virginia South FIPS 4702 (US Feet)
Vertical Datum: NAVD 1988
END DESCRIPTION:
DSS Export Rating Curves= 0
DSS Export Rating Curve Sorted= 0
DSS Export Volume Flow Curves= 0
DXF Filename=.\Hec_working\MFReedyCrk.
DXF OffsetX= 0
DXF OffsetY= 0
DXF ScaleX= 0
DXF ScaleY= 0

--- MFReedyCrk.p01 (plan) ---

Plan Title=Floodplain
Program Version=4.00
Geom File=g01
Flow File=f01
K Sum by GR=0
Std Step Tol=0.01
Critical Tol=0.01
Num of Std Step Trials=20
Max Error Tol=0.3
Flow Tol Ratio=0.001
Split Flow NTrial=30
Split Flow Tol=0.02
Split Flow Ratio=0.02
Log Output Level=0
Friction Slope Method=1
Unsteady Friction Slope Method=2
Unsteady Bridges Friction Slope Method=1
Global Log Level=0
CheckData=False
Run HTab=0
Run UNet=0
Run PostProcess=0
UNET Theta=0
UNET Theta Warmup=0
UNET ZTol=0
UNET ZSATol=0
UNET MxIter=0
UNET MaxInSteps=0
UNET DtIC=0
UNET DtMin=0
UNET MaxCRTS=0
UNET WFStab=0
UNET SFStab=0
UNET WFX=0
UNET SFX=0
UNET DSS MLevel=0
UNET DZMax Abort=0
UNET Convert EG Bridges=0
UNET Use Existing IB Tables=0
UNET Froude Limit=0
UNET Froude Power=0
Write IC File=0
Echo Input=False
Echo Output=False
Write Detailed=0

--- MFReedyCrk.f01 (steady flow) ---

Flow Title=NFF Regression Equation
Program Version=4.10
Number of Profiles= 1
Profile Names=P100yr
River Rch & RM=MFReedyCrk,Main            ,57747.1
888.6882
River Rch & RM=MFReedyCrk,Main            ,57040.6
894.6682
River Rch & RM=MFReedyCrk,Main            ,56284.2
987.8857
River Rch & RM=MFReedyCrk,Main            ,53593
1074.293
River Rch & RM=MFReedyCrk,Main            ,52290.1
1178.452
River Rch & RM=MFReedyCrk,Main            ,51188.9
1295.857
River Rch & RM=MFReedyCrk,Main            ,49189
1427.435
River Rch & RM=MFReedyCrk,Main            ,47184.8
1557.952
River Rch & RM=MFReedyCrk,Main            ,46743.2
1614.526
River Rch & RM=MFReedyCrk,Main            ,45017.4
1772.399
River Rch & RM=MFReedyCrk,Main            ,37087.1
1919.612
River Rch & RM=MFReedyCrk,Main            ,36224.7
2252.696
River Rch & RM=MFReedyCrk,Main            ,35894.8
2395.672
River Rch & RM=MFReedyCrk,Main            ,32015.6
2540.042
River Rch & RM=MFReedyCrk,Main            ,25244.8
 2734.71
River Rch & RM=MFReedyCrk,Main            ,22486.3
3037.982
River Rch & RM=MFReedyCrk,Main            ,19055.3
3320.918
River Rch & RM=MFReedyCrk,Main            ,12787.6
3630.632
River Rch & RM=MFReedyCrk,Main            ,514.9
4033.903
River Rch & RM=MFReedyCrk,Main            ,13.9
4038.224
Boundary for River Rch & Prof#=MFReedyCrk,Main            , 1
Up Type= 0
Dn Type= 1
Dn Known WS=680
DSS Import GetInterval= 0
DSS Import GetPeak= 0
DSS Import FillOption= 0

--- MFReedyCrk.g01 (geometry) ---

Geom Title=USGS 3m DEM
Program Version=4.10

River Reach=MFReedyCrk      ,Main
Reach XY= 30
     1831130.473      650451.321     1831540.162      653056.453
     1831085.014      654807.052     1832877.201      656635.965
      1832797.21      658064.205     1833667.226      659367.917
      1835091.29      660314.543     1835504.564      661337.516
     1835571.225      664768.654     1836914.429      666652.069
     1836362.556      668142.858     1837279.198      669141.434
     1838498.143      669547.351     1838386.959      669983.269
     1839380.322      670856.928     1839593.893      671563.804
     1838841.713      673849.325     1840455.015      675914.451
     1840037.153       676934.48     1841995.304      678995.583
     1842050.766      680588.203      1843113.66      680697.696
     1844185.152      682022.929     1844819.097      681701.671
     1845541.516      682792.415     1845482.383      683957.786
     1844733.808      685015.528     1847059.131      687379.347
     1846895.758      688996.276     1847963.768      690522.983

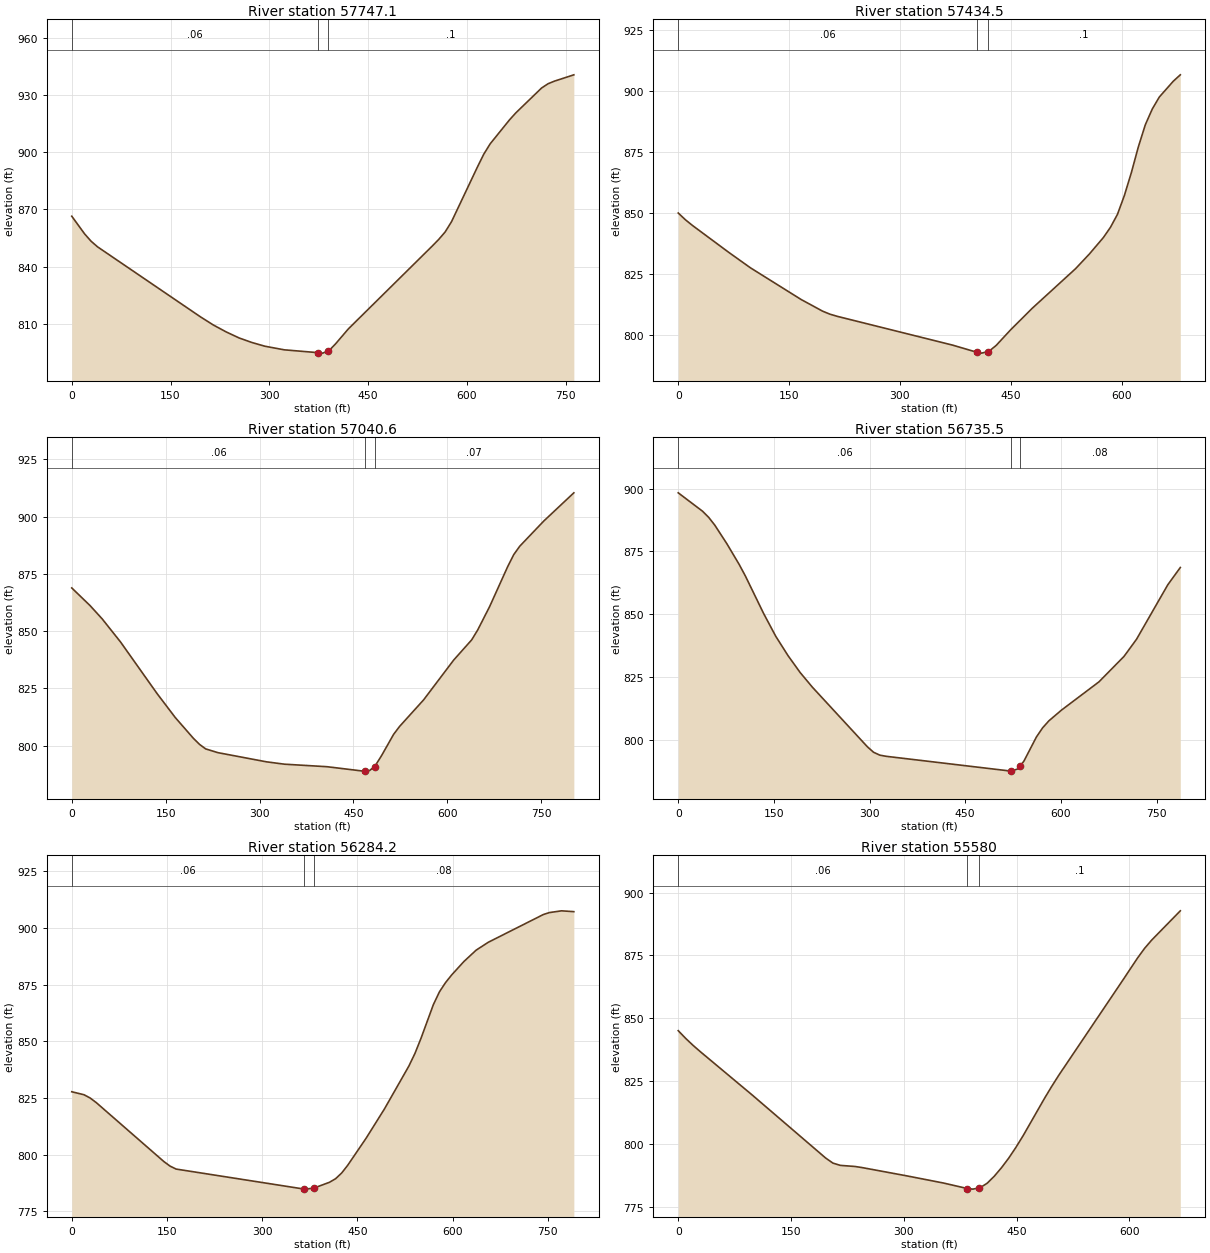
Type RM Length L Ch R = 1 ,57747.1 ,311.3,312.7,312.6
XS GIS Cut Line= 3
     1830779.767      650605.337     1831132.642      650461.083
      1831492.15      650333.765
#Sta/Elev= 30
       0  866.46    19.6  857.15    29.3  853.37    39.1  850.42   195.5   813.7
     215  809.44   234.6   805.8   254.2  802.64   273.7  800.25   293.2  798.32
   322.6  796.43   373.7  794.94   381.2  794.69   388.7  795.75     391  796.08
   400.8   799.6   420.3  807.46   547.5  850.81   557.2  854.23     567  858.15
   576.8  863.58   615.9  892.06   625.7  898.92   635.5   904.4   664.8  916.93
   674.6  920.66   713.7  933.69   723.5   935.9   733.3  937.28   762.6  940.57
#Mann= 3 , 0 , 0
       0     .06       0   373.7    .045       0   388.7      .1       0
Bank Sta=373.7,388.7
XS Rating Curve= 0 ,0
Exp/Cntr=0.3,0.1

Type RM Length L Ch R = 1 ,57434.5 ,389.9,393.9,398.7
XS GIS Cut Line= 3
     1830886.578      650863.276     1831386.578      650693.832
     1831489.356      650582.721
#Sta/Elev= 30
       0  850.14     9.8  847.35    19.6  844.96    68.4     834    97.8  827.65
   166.2  814.69   195.5  809.87   205.3  808.66   215.1  807.78   371.5  795.95
     404  793.05   410.6  792.69     419  793.33   420.4  793.44   430.2  795.86
   449.7  802.24     479  811.09   537.4  827.26   556.3  833.34   575.2  840.08
   584.7  844.23   594.2  849.55   603.6   857.3   613.1  866.73   622.5  877.23
     632  886.36   641.4  892.79   650.9   897.7   669.8  904.18   679.3   906.8
#Mann= 3 , 0 , 0
       0     .06       0     404    .045       0     419      .1       0
Bank Sta=404,419
XS Rating Curve= 0 ,0
Exp/Cntr=0.3,0.1

Type RM Length L Ch R = 1 ,57040.6 ,305.5,305.1,303.9
XS GIS Cut Line= 4
     1830992.134      651177.165     1831187.114      651116.628
     1831474.181      651070.746     1831781.023      651082.721
#Sta/Elev= 30
       0  868.82    29.2  861.12    48.6   855.3    77.8  845.26   136.1  822.76
   165.3  812.24   194.4  803.12   204.2  800.48   213.8  798.55   233.2  796.91
   310.8   792.9   339.8  791.86   407.7  790.76   465.8  788.83   468.9   788.9
   475.5  789.05   483.9  790.83   494.9  795.62   514.1  804.89   523.7  808.36
     562  819.94     610   837.3   638.8  846.14   648.4  850.45   667.6  860.74
   696.4  878.17     706  883.36   715.6  887.04     754  898.04     802  910.35
#Mann= 3 , 0 , 0
       0     .06       0   468.9    .045       0   483.9     .07       0
Bank Sta=468.9,483.9
XS Rating Curve= 0 ,0
Exp/Cntr=0.3,0.1

Type RM Length L Ch R = 1 ,56735.5 ,442.6,451.3,456.7
XS GIS Cut Line= 3
     1830928.245      651385.498     1831214.356      651404.943
       1831708.8      651327.165
#Sta/Elev= 30
       0  898.31    38.2  890.97    47.8  888.53    57.4  885.42    76.5  877.96
    95.6   869.8   105.2  865.26   133.8  850.34   152.9  841.23   172.1  833.55
   191.2  826.79   210.3  820.98   296.6  797.25   306.4  795.05   316.2  793.92
     326  793.46   521.3  787.58   522.3  787.56   532.1  788.41   536.3  789.72
   541.9  791.47   561.6  801.12   571.4  804.79   581.2  807.57   600.8  811.81
   659.7  823.08     699  833.21   718.6  840.02   767.7  861.73   787.3  868.59
#Mann= 3 , 0 , 0
       0     .06       0   521.3    .045       0   536.3     .08       0
Bank Sta=521.3,536.3
XS Rating Curve= 0 ,0
Exp/Cntr=0.3,0.1

Type RM Length L Ch R = 1 ,56284.2 ,709.6,704.2,698.1
XS GIS Cut Line= 3
     1831072.229      651811.998     1831468.133      651791.818
     1831859.393      651843.484
#Sta/Elev= 30
       0  827.74    19.3  826.42      29  824.97    38.7  822.93     145  796.98
   154.7  794.97   164.4  793.64   366.2  784.81   367.4  784.79   381.2  785.22
     406   787.8   415.7  789.38   425.3  791.91   434.9  795.35   463.8  807.25
   492.7  820.17   531.2  839.09   540.8  844.68   550.4   851.4   569.7  866.13
   579.3  871.79   588.9  875.87   598.6  879.26   617.8  885.16   637.1  890.18
   656.3  893.67     743   905.9   752.6  906.77   771.8  907.54   791.1  907.17
#Mann= 3 , 0 , 0
       0     .06       0   366.2    .045       0   381.2     .08       0
Bank Sta=366.2,381.2
XS Rating Curve= 0 ,0
Exp/Cntr=0.3,0.1

Type RM Length L Ch R = 1 ,55580   ,330.2,330.6,332.6
XS GIS Cut Line= 3
     1831074.953      652482.721     1831466.642      652468.103
     1831740.107      652431.556
#Sta/Elev= 30
       0  845.08     9.8  842.04    19.6  839.27    29.4  836.72      98  819.59
     196  794.44   205.8  792.39   215.6  791.49   235.2  791.05     245  790.59
   303.8  787.33   352.8  784.47   384.5  782.28     392  782.04   399.5  782.48
   401.5   782.6     411  784.39   420.5   787.2     430  790.55   439.5  794.32
     449  798.56   458.6  803.19   487.1  818.08   496.6   822.8   506.1  827.28
   591.8  865.34   610.8   873.9   620.3   877.8   629.8  881.11   667.9  892.76
#Mann= 3 , 0 , 0
       0     .06       0   384.5    .045       0   399.5      .1       0
Bank Sta=384.5,399.5
XS Rating Curve= 0 ,0
Exp/Cntr=0.3,0.1

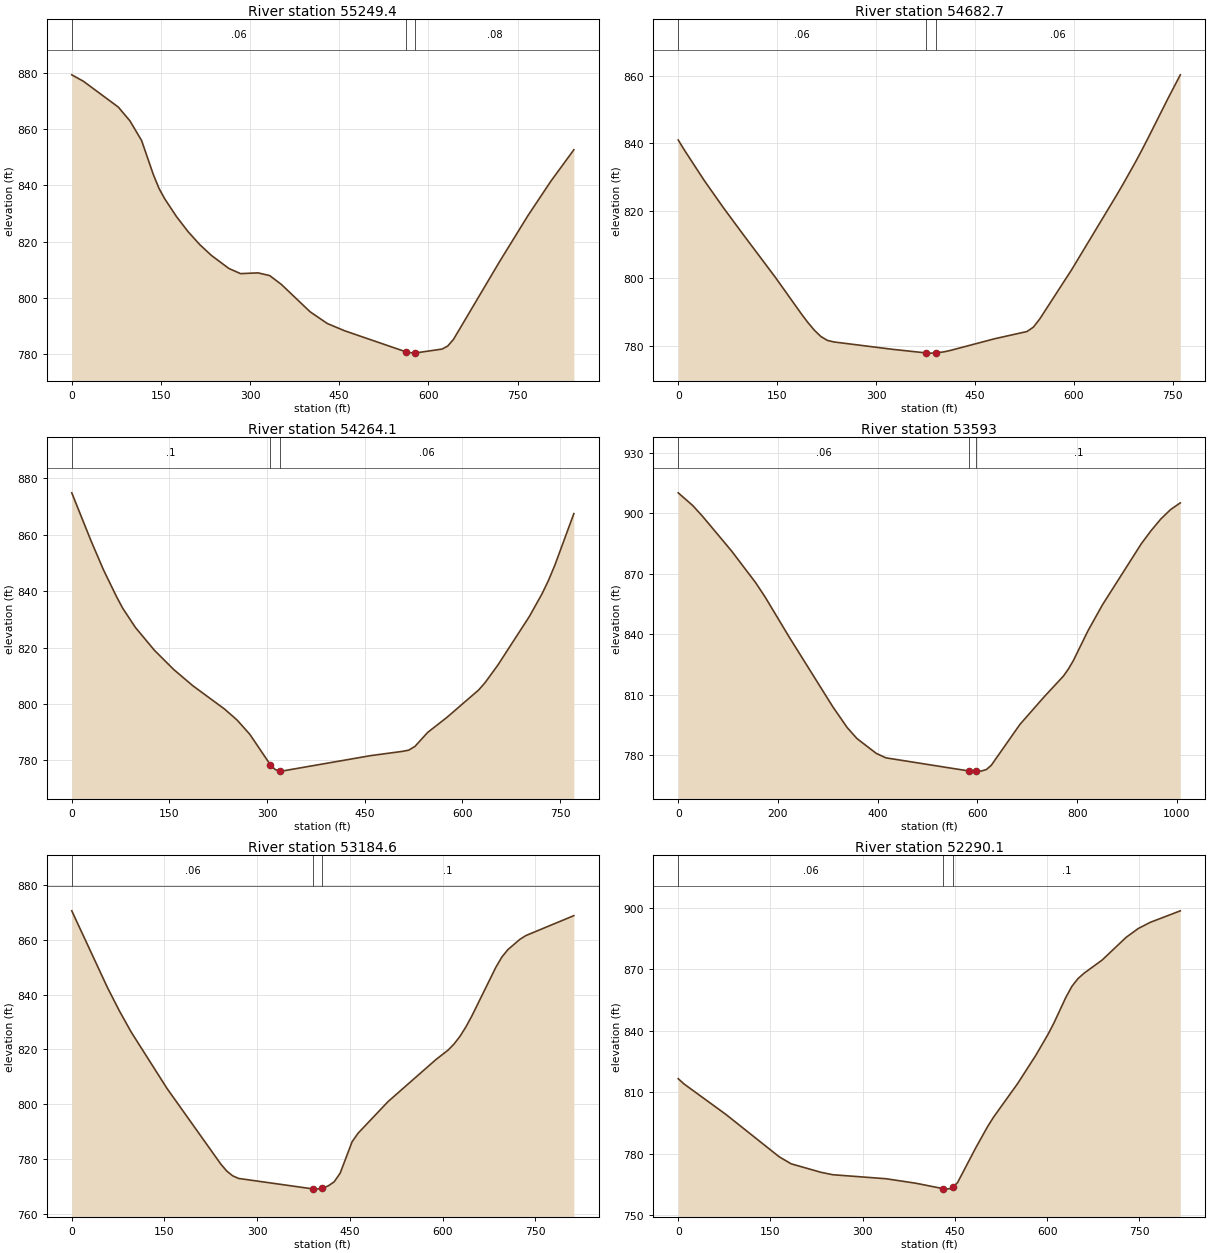
Type RM Length L Ch R = 1 ,55249.4 ,558.1,566.7,570.7
XS GIS Cut Line= 3
     1830942.134      653002.165     1831256.023      652802.165
     1831728.245      652782.721
#Sta/Elev= 30
       0  879.37    19.6  877.08    78.4  867.87      98  862.94   117.5  855.98
   137.1  843.95   146.9  838.89   156.7  835.14   176.3  828.87   195.9  823.49
   215.5   818.9   235.1  815.05   264.4  810.43     284  808.59   313.4  808.86
     333   807.9   352.6  804.76   401.1     795   430.1  790.82     459  788.26
   562.8  780.71   574.7  780.29   577.8  780.34     623  781.73   632.6  782.81
   642.3  785.19   719.4  812.72   767.6  829.26   806.2  841.52   844.8  852.69
#Mann= 3 , 0 , 0
       0     .06       0   562.8    .045       0   577.8     .08       0
Bank Sta=562.8,577.8
XS Rating Curve= 0 ,0
Exp/Cntr=0.3,0.1

Type RM Length L Ch R = 1 ,54682.7 ,422.6,418.6,419.4
XS GIS Cut Line= 3
     1831071.018      653163.618     1831435.526      653282.789
     1831807.015      653352.537
#Sta/Elev= 30
       0  840.92     9.8  837.82    39.3  828.99    68.8  820.81    98.3  813.02
   147.5  800.23   186.8  789.46   196.7   786.9   206.5  784.63   216.3  782.78
   226.2  781.62     236  781.16   324.5  778.99     376  777.91   383.5  777.85
     391  777.93   402.9  778.22   412.6  778.64   480.4  782.13   528.9  784.24
   538.6  785.53   548.3  787.96   596.7  802.54   664.6  824.51   674.2  827.71
   693.6  834.44   703.3  837.99     713  841.66   742.1  852.95   761.5  860.22
#Mann= 3 , 0 , 0
       0     .06       0     376    .045       0     391     .06       0
Bank Sta=376,391
XS Rating Curve= 0 ,0
Exp/Cntr=0.3,0.1

Type RM Length L Ch R = 1 ,54264.1 ,670.1,671.1,666.7
XS GIS Cut Line= 3
     1830956.879        653557.2     1831268.011      653586.698
     1831712.556      653698.889
#Sta/Elev= 30
       0  874.87    29.3  858.01    48.8  847.51    68.4  838.21    78.1     834
    97.7  827.14     127  819.02   156.3  812.28   185.6  806.52   234.4  798.24
   253.9   794.3   273.5  789.22     305  778.44   312.5  776.72     320  776.31
   322.3  776.19   458.8  781.68   507.6  783.19   517.4  783.62   527.1  784.98
   546.6  789.93   575.9  795.21   624.7  804.94   634.4  807.48     654  813.68
   702.7  831.03   722.2  839.09     732  843.79   741.8  849.19     771   867.5
#Mann= 3 , 0 , 0
       0      .1       0     305    .045       0     320     .06       0
Bank Sta=305,320
XS Rating Curve= 0 ,0
Exp/Cntr=0.3,0.1

Type RM Length L Ch R = 1 ,53593   ,402.6,408.5,413.3
XS GIS Cut Line= 4
     1830811.578      654310.498     1831178.245      654157.721
       1831483.8      654191.054     1831767.134      654085.498
#Sta/Elev= 30
       0  910.25    29.1  903.94    48.4  898.69   106.6  881.46     155  865.69
   174.4  858.42   222.8  838.47     310  803.92   339.1   793.5   358.5   788.1
   397.2  780.74   416.4  778.53   582.9     772   589.3  771.92   597.9  771.93
   608.5  772.01   618.1  772.72   627.8   774.8   685.4  795.17   733.8  808.81
   772.9  819.26   782.6   822.7   792.4  826.83   821.6  841.58   850.9  854.61
   928.9     885   948.4  891.46   967.9  897.24   987.4  901.91    1007  905.26
#Mann= 3 , 0 , 0
       0     .06       0   582.9    .045       0   597.9      .1       0
Bank Sta=582.9,597.9
XS Rating Curve= 0 ,0
Exp/Cntr=0.3,0.1

Type RM Length L Ch R = 1 ,53184.6 ,910.1,894.5,880.5
XS GIS Cut Line= 3
     1830901.777        654403.4     1831267.808      654552.961
      1831661.39      654690.715
#Sta/Elev= 30
       0  870.62    57.9  842.54    77.2  834.03    96.4  826.27   154.3  805.72
   241.1  778.18   250.8  775.62   260.4  773.87     270  772.92   390.6  769.09
   395.4  769.02   405.6  769.35   414.8  770.18   424.5  771.67   434.2  774.81
   453.6  786.32   463.3  789.44   511.8  800.98   589.4  816.35   608.8  819.74
   618.4  821.97   628.2  824.81   637.8  828.27   647.5  832.29   686.3  850.05
     696  853.76   705.7  856.46   725.1  860.21   734.8  861.59   812.4  868.86
#Mann= 3 , 0 , 0
       0     .06       0   390.6    .045       0   405.6      .1       0
Bank Sta=390.6,405.6
XS Rating Curve= 0 ,0
Exp/Cntr=0.3,0.1

Type RM Length L Ch R = 1 ,52290.1 ,515.1,515.9,514.3
XS GIS Cut Line= 3
      1831053.42      655262.582     1831482.424      655113.021
     1831840.583      655057.919
#Sta/Elev= 30
       0  816.54     9.7  813.92    77.3  799.18   164.3  778.43   183.7  775.02
     232  770.89   251.3   769.7   338.3  767.73   386.7  765.54   431.4  762.87
     435  762.67   444.7  763.02   446.4  763.52   454.3  765.83   483.7  782.69
   503.3  793.21   513.1  797.88   552.3  814.27   581.6  827.95   601.2  838.03
     611  843.66   630.6   856.3   640.4  861.62   650.2  865.37     660  867.99
   689.4  874.41   728.6  885.53   748.1  889.79   767.7  892.83   816.7  898.46
#Mann= 3 , 0 , 0
       0     .06       0   431.4    .045       0   446.4      .1       0
Bank Sta=431.4,446.4
XS Rating Curve= 0 ,0
Exp/Cntr=0.3,0.1

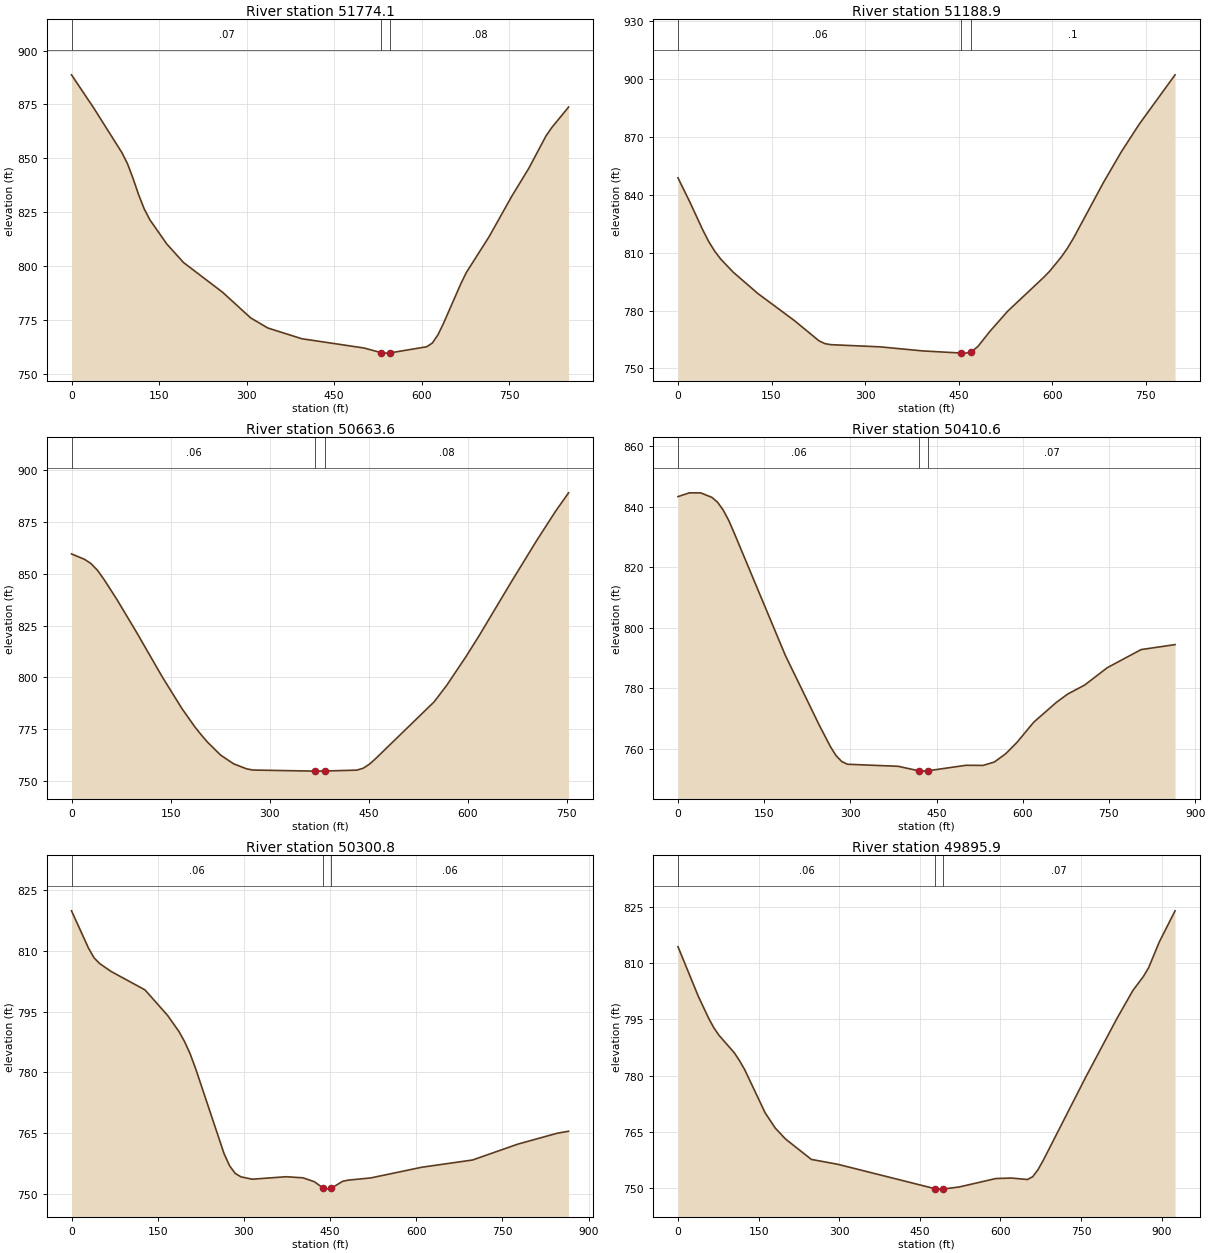
Type RM Length L Ch R = 1 ,51774.1 ,597.3,585.3,572
XS GIS Cut Line= 3
     1831025.467      655679.943     1831322.689      655691.054
     1831842.134       655496.61
#Sta/Elev= 30
       0  888.71    38.4  873.18    86.4  852.58      96  847.42   105.5  840.61
   115.1  833.01   124.7  826.42   134.3  821.42   163.1  810.25   191.9  801.59
     259  787.76   307.2  775.84   336.4  771.18   394.7  766.19   501.8  761.86
   531.2  759.68   540.7   759.5   546.2  759.62   608.8  762.45   618.5  764.18
   628.3  768.06     638  773.51   667.2   791.6   676.9  796.96   715.8  813.54
   754.8  832.37     784  845.35   813.2  860.24   822.9   864.1   852.1  873.75
#Mann= 3 , 0 , 0
       0     .07       0   531.2    .045       0   546.2     .08       0
Bank Sta=531.2,546.2
XS Rating Curve= 0 ,0
Exp/Cntr=0.3,0.1

Type RM Length L Ch R = 1 ,51188.9 ,527.8,525.3,522.4
XS GIS Cut Line= 3
     1831657.454      656375.245     1831945.053       656014.04
     1832145.496      655745.514
#Sta/Elev= 30
       0  848.84    19.6  835.91    39.3  822.13    49.1  815.91    58.9  810.79
    68.8   806.6    88.4  799.96   127.7  788.94   186.6  774.82     226  764.33
   235.8  762.84   245.6  762.32   324.2  761.19     393  759.07   454.2  757.98
   461.7  757.94   469.2  758.66   471.3  758.86   480.9  761.44     500  769.22
   528.7  779.75   586.2  797.22   595.8  800.41   614.9  807.98   624.5  812.45
     634  817.57   681.9  846.34   710.6  862.29   739.4  876.67   796.8  902.26
#Mann= 3 , 0 , 0
       0     .06       0   454.2    .045       0   469.2      .1       0
Bank Sta=454.2,469.2
XS Rating Curve= 0 ,0
Exp/Cntr=0.3,0.1

Type RM Length L Ch R = 1 ,50663.6 ,238.9,253,256.7
XS GIS Cut Line= 3
     1832157.605      656641.287     1832393.153      656244.532
     1832496.086      655972.198
#Sta/Elev= 30
       0  859.51    19.6  856.92    29.4  854.88    39.3  851.63    49.1  847.27
    68.7  837.58    98.2  821.91   137.4  800.29   166.9  785.16   186.5   776.3
   196.3   772.4   206.2  768.74   225.8   762.6   245.4  758.41   265.1  755.98
   274.9   755.4   369.4  754.88   384.4  754.95     432  755.36   441.8   756.3
   451.6  758.35   461.4  761.19   548.8  788.18   568.2  796.25   597.3  810.08
   616.7  819.87   665.2  845.68     704  865.81   733.1  880.16   752.6  888.94
#Mann= 3 , 0 , 0
       0     .06       0   369.4    .045       0   384.4     .08       0
Bank Sta=369.4,384.4
XS Rating Curve= 0 ,0
Exp/Cntr=0.3,0.1

Type RM Length L Ch R = 1 ,50410.6 ,120,109.9,108.6
XS GIS Cut Line= 2
     1832276.533      656745.334     1832830.451      656080.972
#Sta/Elev= 30
       0  843.33    19.7  844.57    39.3  844.58      59  843.08    68.8  841.49
    78.6  838.92    88.5   835.4    98.3   831.1   186.8   790.9   245.7   767.9
   265.4   760.7   275.2  757.74     285  755.81   294.9  754.93   383.4  754.24
   419.8  752.72   422.7  752.65   434.8  752.76   501.3  754.58   530.8  754.54
   550.4  755.64   570.1  758.36   589.8  762.12   619.2  768.84   658.6  775.38
   678.2  778.11   707.7  781.08     747  786.81     806   792.8     865  794.44
#Mann= 3 , 0 , 0
       0     .06       0   419.8    .045       0   434.8     .07       0
Bank Sta=419.8,434.8
XS Rating Curve= 0 ,0
Exp/Cntr=0.3,0.1

Type RM Length L Ch R = 1 ,50300.8 ,385,404.9,421.9
XS GIS Cut Line= 2
     1832355.772      656818.839      1832909.69      656154.477
#Sta/Elev= 30
       0  819.86    29.5  810.68    39.3  808.24    49.2  806.82    68.8   804.9
   127.8  800.35   167.1  794.06   186.8  790.11   196.6  787.62   206.4  784.57
   216.2  780.83   265.4  759.94   275.2  756.89     285  755.03   294.9  754.19
   314.5  753.61   373.5  754.22     403  753.95   422.7  752.98     437  751.52
   442.3  751.16     452  751.38   471.8  753.09   481.6  753.38     521  753.93
   609.4  756.56   697.9  758.35   776.5  762.26   845.3  764.96     865  765.45
#Mann= 3 , 0 , 0
       0     .06       0     437    .045       0     452     .06       0
Bank Sta=437,452
XS Rating Curve= 0 ,0
Exp/Cntr=0.3,0.1

Type RM Length L Ch R = 1 ,49895.9 ,697,706.9,702.6
XS GIS Cut Line= 3
     1832389.755      656847.724      1832595.35      656727.086
     1833281.627      656709.927
#Sta/Elev= 30
       0  814.43    38.1  801.09    57.2  795.28    66.8  792.76    76.3  790.76
   104.9  786.07   114.4     784     124  781.62   162.1  770.06   181.2  765.93
   200.2  763.03   248.2  757.59   297.2  756.29   478.1  749.77   483.6  749.65
   493.1  749.68   522.8  750.21   591.4  752.48   620.8  752.61   650.3  752.22
   660.1  752.98   669.9  754.85   679.7  757.35   758.2  779.44     817  795.31
   846.4  802.72     866  806.47   875.8  808.84   895.4  815.64   924.9  824.02
#Mann= 3 , 0 , 0
       0     .06       0   478.1    .045       0   493.1     .07       0
Bank Sta=478.1,493.1
XS Rating Curve= 0 ,0
Exp/Cntr=0.3,0.1

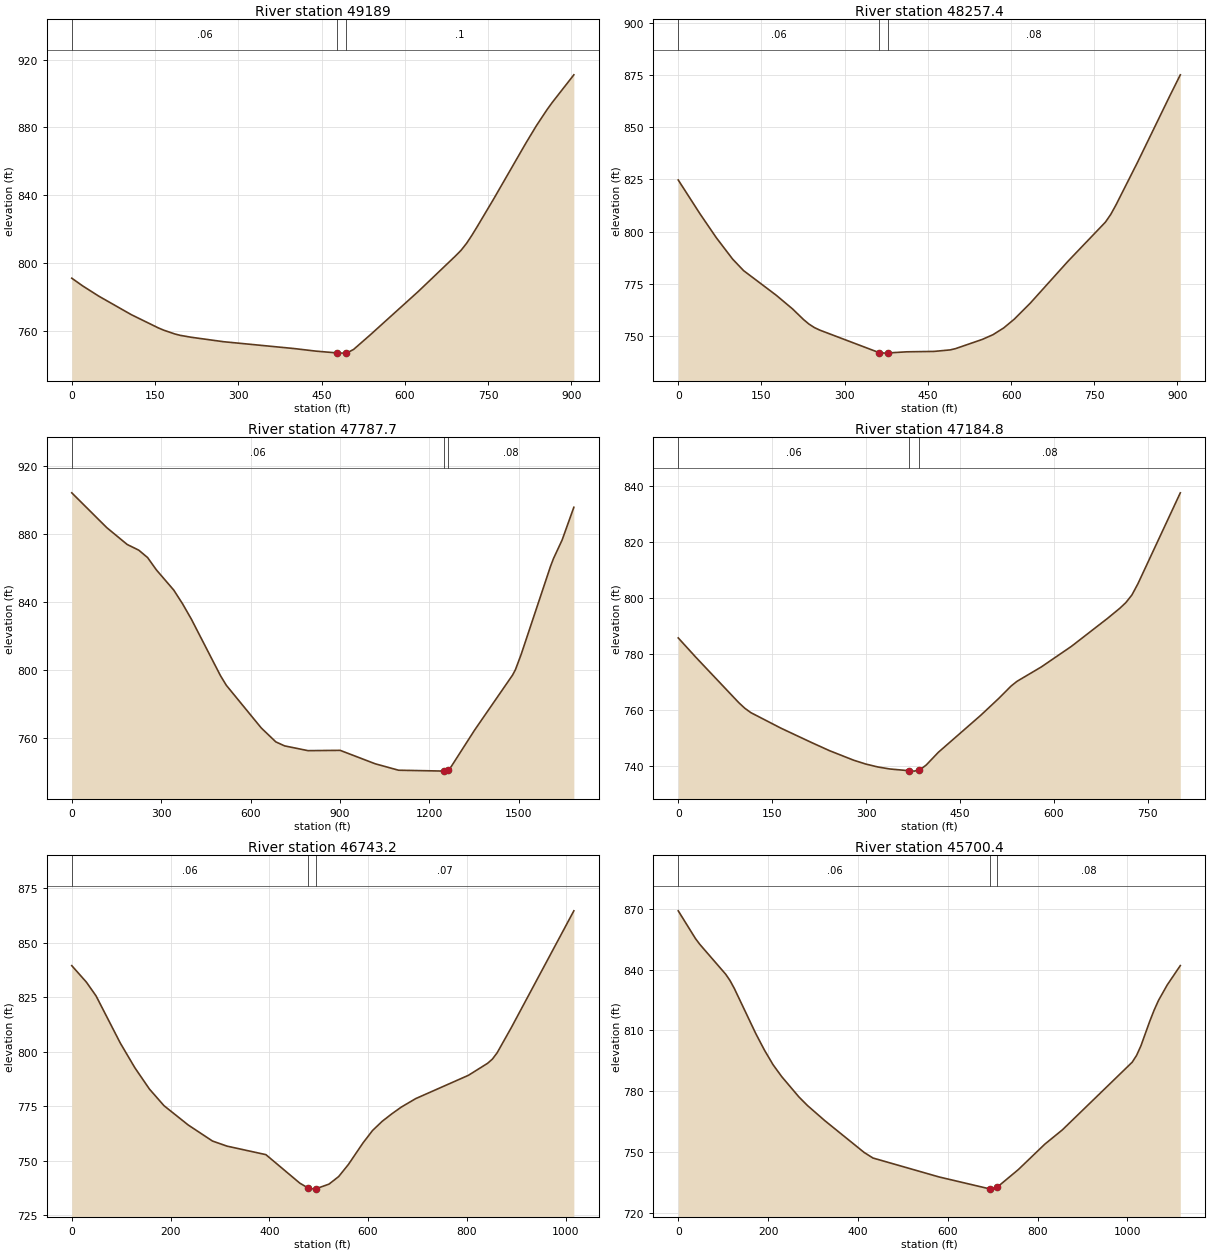
Type RM Length L Ch R = 1 ,49189   ,937.8,931.6,932
XS GIS Cut Line= 3
     1832469.162      657320.032      1833014.96      657284.927
     1833370.464      657323.968
#Sta/Elev= 30
       0  791.25    19.5  786.74    48.8  780.65   107.4  769.75   156.3  761.92
     166   760.6   185.6  758.41   195.3   757.6   214.9  756.48   273.5  753.84
   400.4  749.82   439.5  748.31   478.4  747.22   488.3  747.12   493.4  747.38
   498.1  747.62   507.9  749.33   537.2   757.7   624.2  783.39   691.9  804.52
   701.6  807.75   711.2  811.73   720.9  816.51   730.6  821.68   759.6  837.61
   817.6  870.48   836.9  880.94   856.2  890.47   865.9  894.84   904.6  911.02
#Mann= 3 , 0 , 0
       0     .06       0   478.4    .045       0   493.4      .1       0
Bank Sta=478.4,493.4
XS Rating Curve= 0 ,0
Exp/Cntr=0.3,0.1

Type RM Length L Ch R = 1 ,48257.4 ,479.6,469.7,456.3
XS GIS Cut Line= 3
     1832427.238      658043.942     1832898.129      658056.696
      1833328.54      658000.648
#Sta/Elev= 30
       0  824.69    39.3  808.48    68.7  797.05    98.1  786.82   117.8  781.32
   176.6  769.55   206.1  762.98   225.7  757.95   235.5  755.77   245.4  754.06
   255.2  752.84   362.7  742.01   372.9  741.83   377.7  741.91   412.2  742.46
   461.2  742.65   490.4  743.38     500  743.99   548.2   748.4   567.5  750.67
   586.8   753.9   606.1  758.16     635  765.86   702.6  785.79   770.1  804.53
   779.7  808.22   789.4   812.9     828  833.18   885.8  864.75   905.1  875.03
#Mann= 3 , 0 , 0
       0     .06       0   362.7    .045       0   377.7     .08       0
Bank Sta=362.7,377.7
XS Rating Curve= 0 ,0
Exp/Cntr=0.3,0.1

Type RM Length L Ch R = 1 ,47787.7 ,609.1,602.9,596
XS GIS Cut Line= 3
      1832052.46      659066.177      1832596.21      658666.177
      1833464.96      658151.593
#Sta/Elev= 30
       0  904.06   117.4  883.61   185.9  873.72     225  870.34   254.4  866.03
   283.7  858.83   342.4  846.87   371.8  838.85   401.1   829.9   498.9  796.64
   518.5  790.99   635.9  765.88   684.8   757.7   714.2  755.36   792.7  752.56
   900.5  752.74  1018.1  744.85  1096.6  741.06  1248.3  740.56  1253.4  740.53
  1263.3  741.09    1273  743.14  1351.4  764.56  1478.9  796.92  1488.7  800.14
  1508.3  809.31  1606.3   860.8  1616.1  865.33  1645.5   876.4  1684.7  895.57
#Mann= 3 , 0 , 0
       0     .06       0  1248.3    .045       0  1263.3     .08       0
Bank Sta=1248.3,1263.3
XS Rating Curve= 0 ,0
Exp/Cntr=0.3,0.1

Type RM Length L Ch R = 1 ,47184.8 ,442.8,441.6,439.5
XS GIS Cut Line= 3
     1833095.672      659155.346     1833397.638      658842.299
     1833670.301      658596.459
#Sta/Elev= 30
       0  785.86      29  778.74    96.7  762.72   106.3  760.73     116  759.15
   164.3  753.57   212.6   748.5   241.6  745.56   280.3  742.14   299.6  740.77
     319  739.72   338.3     739   368.9  738.38     377  738.24   383.9  738.64
   386.6   738.8   396.3  740.45   415.6  744.98   483.3   758.2   512.2  764.26
   531.6  768.62   541.2  770.34   579.9  775.46   628.2  782.85   686.1  792.89
   705.5  796.46   715.1  798.48   724.8  801.22   734.4  805.22   802.1  837.72
#Mann= 3 , 0 , 0
       0     .06       0   368.9    .045       0   383.9     .08       0
Bank Sta=368.9,383.9
XS Rating Curve= 0 ,0
Exp/Cntr=0.3,0.1

Type RM Length L Ch R = 1 ,46743.2 ,1037,1042.8,1046
XS GIS Cut Line= 3
     1833267.043       659537.01     1833694.127      659116.177
      1834002.46      658834.927
#Sta/Elev= 30
       0  839.54    29.5     832    49.2  825.65    98.3  803.99   127.8  792.65
   157.3  782.88   186.8  775.24   235.9  766.37     285  759.01   314.5  756.67
   393.2  752.76     462  739.66   479.1  737.39   491.5  736.93   494.1  737.06
     521  739.23   540.6   742.7   560.3  748.25   589.8  758.12   609.3  763.87
   628.7  768.06   648.1  771.48   667.5  774.61   696.6  778.49   803.4  789.19
   842.2   794.7   851.9  796.62   861.6  799.55   890.8  811.32  1016.9  864.71
#Mann= 3 , 0 , 0
       0     .06       0   479.1    .045       0   494.1     .07       0
Bank Sta=479.1,494.1
XS Rating Curve= 0 ,0
Exp/Cntr=0.3,0.1

Type RM Length L Ch R = 1 ,45700.4 ,687.5,683,678.6
XS GIS Cut Line= 4
      1833908.71      660053.677     1834087.336        659746.8
      1834458.71      659426.593      1834571.21      659178.677
#Sta/Elev= 30
       0  869.01    38.4  855.32      48  852.48   105.6  837.74   115.2  834.64
   124.8  830.73   172.7  808.41   191.9  800.29   211.1  793.08   230.3  787.22
   268.7  777.17   287.9   772.9   326.3  765.48   413.9  749.78   433.5  747.04
   580.6   737.7   695.1  731.72   698.3  731.69   710.1  732.66   757.2  741.35
     816  753.86   855.2  760.94  1010.7  794.34  1020.4   797.7  1030.2  802.51
  1049.6  814.47  1059.4  819.99  1069.1  824.78  1088.5  832.42  1117.7  841.99
#Mann= 3 , 0 , 0
       0     .06       0   695.1    .045       0   710.1     .08       0
Bank Sta=695.1,710.1
XS Rating Curve= 0 ,0
Exp/Cntr=0.3,0.1

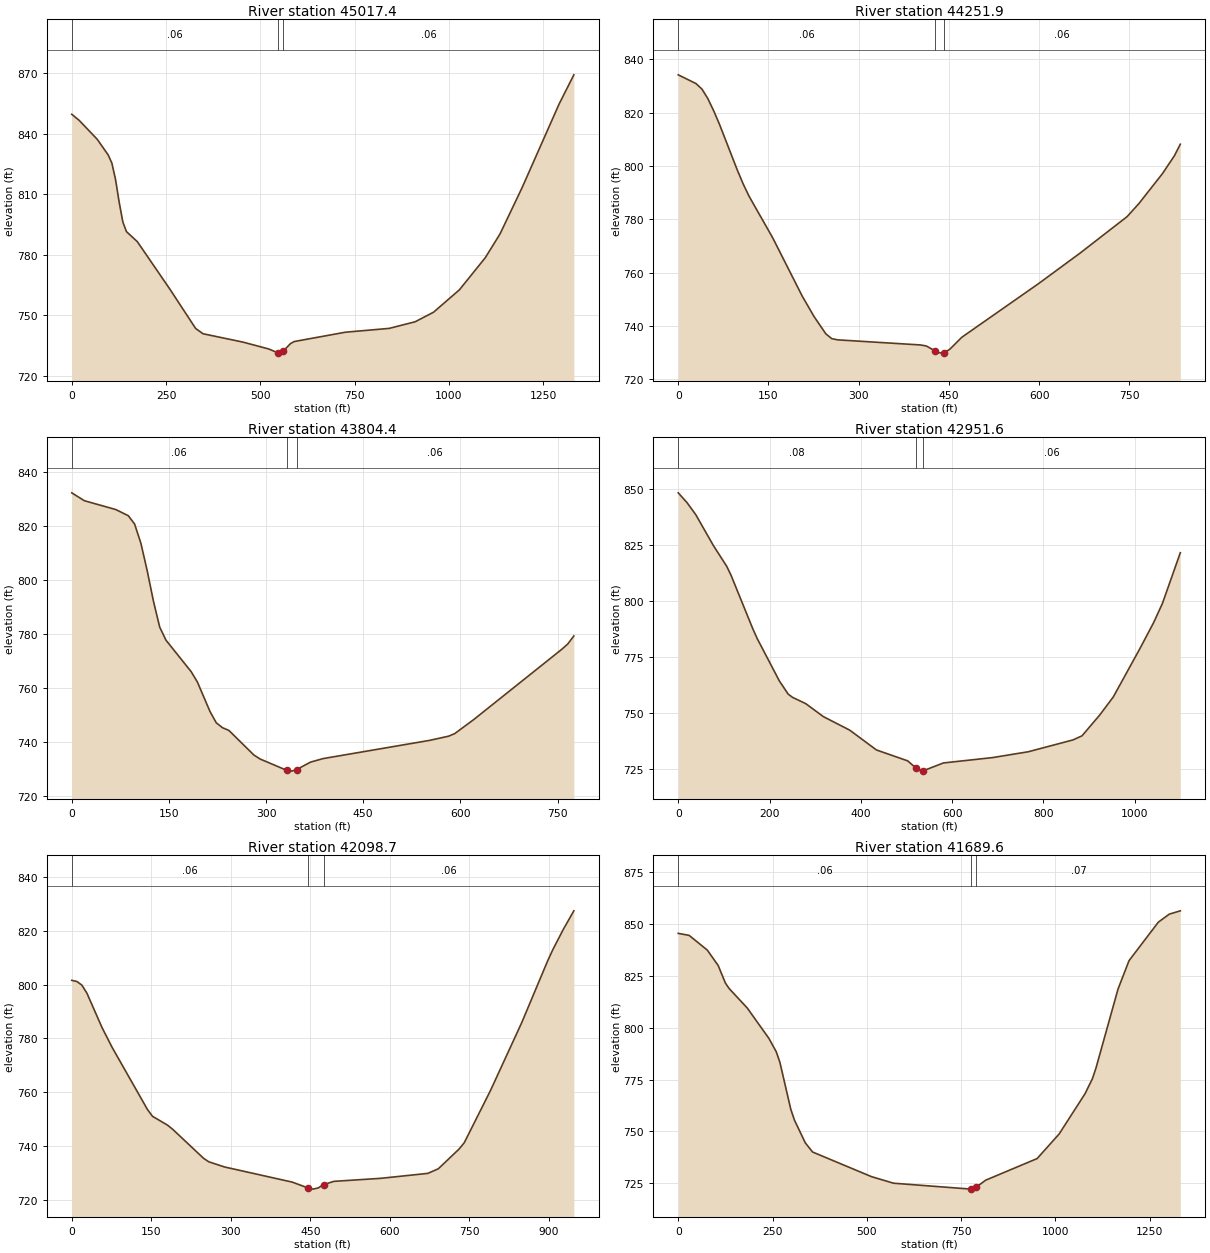
Type RM Length L Ch R = 1 ,45017.4 ,756.7,765.5,773.4
XS GIS Cut Line= 4
     1834537.877      660572.427      1834577.46      660197.427
     1834850.377      659857.843     1835356.627       659743.26
#Sta/Elev= 30
       0  849.68    19.3  846.74    67.7  837.24    96.7  829.48   106.4  825.42
     116  817.44   125.7  806.12   135.4  796.31     145  791.47     174  786.46
   261.1  762.68   328.7  743.38   348.1  740.79   454.5  736.62   522.3  733.24
   546.2  731.37   551.4  731.17   561.2   732.2   580.4  735.95   590.1  736.92
   725.6  741.54   842.1  743.45   910.7  746.72   959.6  751.47  1028.2  762.57
  1096.8  778.49  1135.9  790.28  1194.7  813.34  1292.6  854.72  1331.8  869.26
#Mann= 3 , 0 , 0
       0     .06       0   546.2    .045       0   561.2     .06       0
Bank Sta=546.2,561.2
XS Rating Curve= 0 ,0
Exp/Cntr=0.3,0.1

Type RM Length L Ch R = 1 ,44251.9 ,448.4,447.4,447.2
XS GIS Cut Line= 2
     1834773.293      660797.427     1835494.127      660376.593
#Sta/Elev= 30
       0  834.17    29.5  830.89    39.3  828.85    49.1  825.31    58.9   820.7
    68.7  815.54    98.2  798.45     108  793.21   117.8   788.6   157.1  773.01
   206.2  751.12   225.9  743.45   245.5  736.97   255.3  735.19   265.1  734.74
   402.6  732.83   412.4  732.44     427  730.61   432.1  729.95   441.9  729.76
     442  729.78   451.7  731.26   471.4   735.7     599  755.83   667.8  767.24
   746.3  780.98     766  785.91   805.2  797.16   824.9  803.81   834.7  808.14
#Mann= 3 , 0 , 0
       0     .06       0     427    .045       0     442     .06       0
Bank Sta=427,442
XS Rating Curve= 0 ,0
Exp/Cntr=0.3,0.1

Type RM Length L Ch R = 1 ,43804.4 ,833.2,852.8,871.2
XS GIS Cut Line= 3
     1834979.284      661192.685     1835263.229       661006.53
      1835632.63      660775.489
#Sta/Elev= 30
       0  832.22    19.4   829.3    67.9  826.03    87.3  823.73      97  820.67
   106.7  813.55   116.4  803.43   126.1  792.07   135.8  782.43   145.5  777.59
   184.3  765.95     194  762.07   213.4  751.18   223.1  746.98   232.8  745.14
   242.5  744.17   281.3  735.01     291  733.53     332  729.35   339.5  729.06
     347  729.62   368.6  732.39   387.9   733.7   552.5  740.46   581.6     742
   591.3  742.97   620.3  748.11   755.9  774.09   765.6  776.13   775.2  779.16
#Mann= 3 , 0 , 0
       0     .06       0     332    .045       0     347     .06       0
Bank Sta=332,347
XS Rating Curve= 0 ,0
Exp/Cntr=0.3,0.1

Type RM Length L Ch R = 1 ,42951.6 ,858.5,853,845.6
XS GIS Cut Line= 3
      1834864.96      661745.691     1835248.641      661651.941
     1835932.668      661822.079
#Sta/Elev= 30
       0  848.31    19.3  843.93    38.5  838.54    77.1  824.77     106  815.61
   115.6  811.59   163.8  787.45   173.4  783.15   221.6  764.39   240.8  758.54
   250.5  757.08   279.4  754.28   317.9   748.5   375.7  742.46   434.1  733.64
   502.7  728.76   520.8  725.56     532  724.19   535.8  724.28     581  727.84
   688.7  730.23     767  732.84   864.9  738.12   884.5  739.94   923.6  749.29
     953  757.28  1011.7  778.99  1041.1  790.32  1060.7  799.02  1099.8   821.6
#Mann= 3 , 0 , 0
       0     .08       0   520.8    .045       0   535.8     .06       0
Bank Sta=520.8,535.8
XS Rating Curve= 0 ,0
Exp/Cntr=0.3,0.1

Type RM Length L Ch R = 1 ,42098.7 ,408.1,409,409.2
XS GIS Cut Line= 3
     1834913.571      662221.385     1835094.127      662327.288
      1835825.03      662226.593
#Sta/Elev= 30
       0  801.56     9.5  801.16      19   799.8    28.5  796.83    57.1     784
    76.1  776.65   142.7  753.56   152.2  751.02   180.8  747.69   190.3  746.19
   248.7  735.37   258.5  734.08     288  732.17   415.9  726.53   445.4  724.38
   455.2  723.92   465.1  724.38   474.9   725.6   494.6  726.81   583.1  727.94
   671.7  729.78   691.4  731.48   730.7  738.84   740.5  741.22   789.7  760.53
   848.8  785.84   897.9   808.9   907.8  813.12   927.4  820.59   947.1  827.42
#Mann= 3 , 0 , 0
       0     .06       0   445.4    .045       0   474.9     .06       0
Bank Sta=445.4,474.9
XS Rating Curve= 0 ,0
Exp/Cntr=0.3,0.1

Type RM Length L Ch R = 1 ,41689.6 ,893.5,894.8,883.3
XS GIS Cut Line= 4
     1834772.946      662879.371     1835094.127      662704.024
     1835821.557      662620.691     1836054.196      662636.316
#Sta/Elev= 30
       0  845.44    28.9  844.47      77   837.4   105.9  829.97   125.2  821.46
   134.8   818.9     183  809.48   240.7  794.76     260  788.36   269.6  783.29
   298.5  760.64   308.2  755.44     337  744.48   356.3  740.08   512.4  728.22
   570.9  725.05   775.4  722.22     776   722.2   790.4  723.16     815  726.49
   951.7  736.93  1010.2  748.82  1078.6  768.15  1098.1  775.34  1107.8  780.63
  1166.1  818.56  1195.3  832.28    1273  850.83  1302.1  854.71  1331.3   856.3
#Mann= 3 , 0 , 0
       0     .06       0   775.4    .045       0   790.4     .07       0
Bank Sta=775.4,790.4
XS Rating Curve= 0 ,0
Exp/Cntr=0.3,0.1

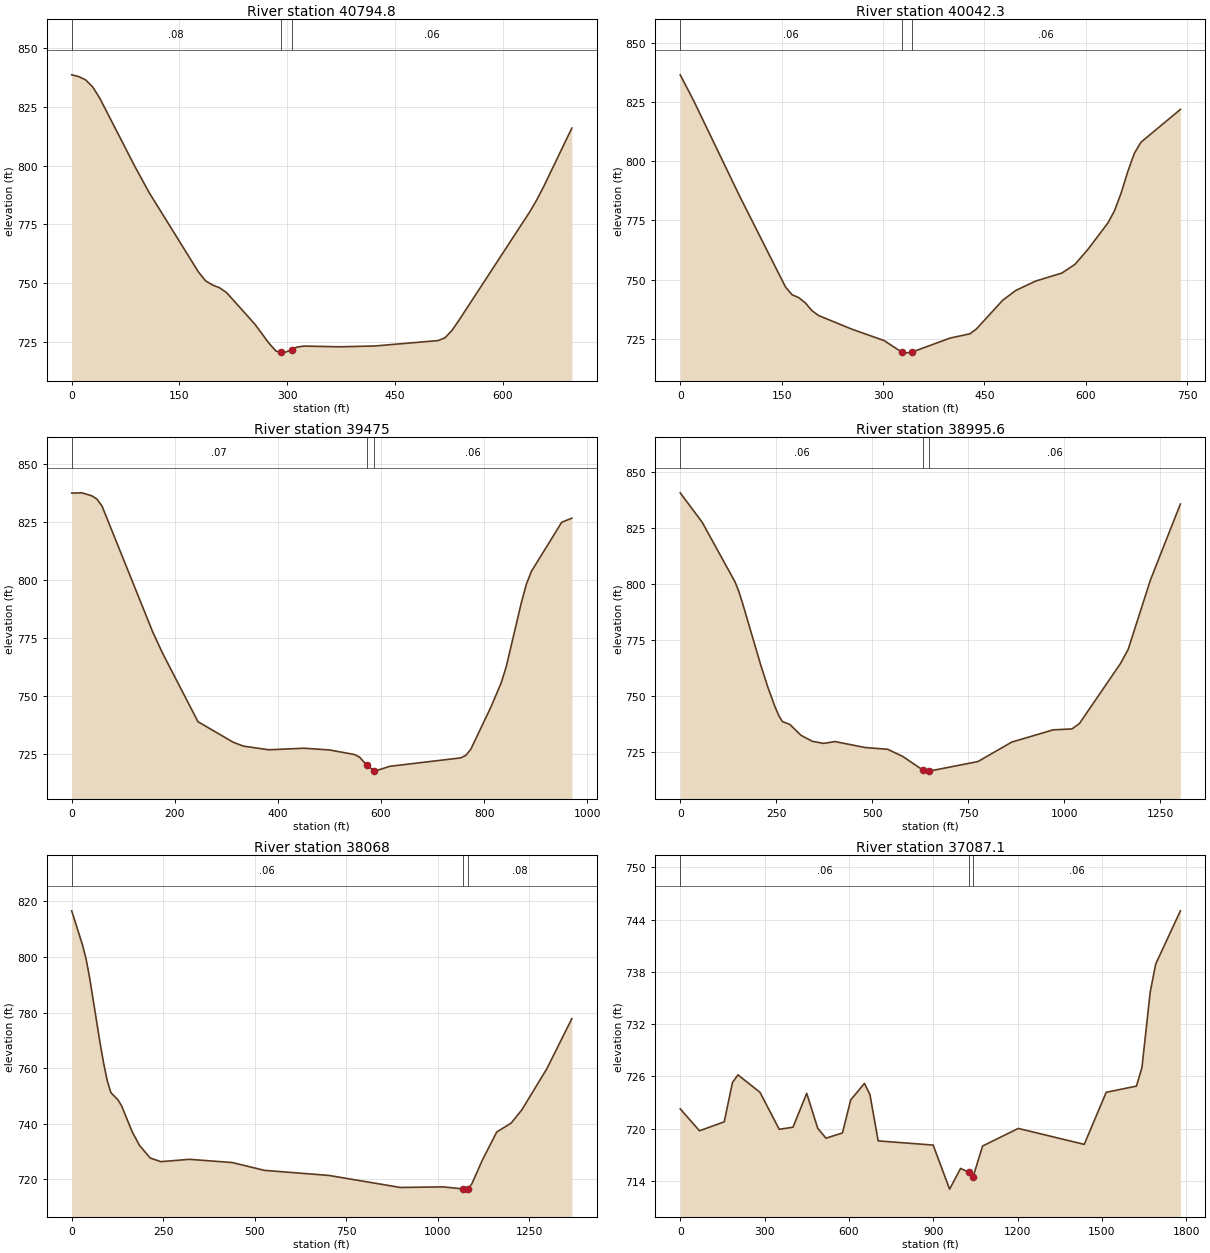
Type RM Length L Ch R = 1 ,40794.8 ,750.7,752.5,754.2
XS GIS Cut Line= 2
     1835176.075      663278.669     1835868.779      663207.824
#Sta/Elev= 30
       0  838.56     9.8  837.82    19.6  836.37    29.4  833.36    39.2  828.57
    88.3  799.41   107.9  788.48   176.5  754.71   186.3  750.99   196.2  749.15
     206     748   215.8  745.89     255  732.54   274.6  724.44   284.4   721.1
   291.1  720.49   294.2  720.21   306.1  721.66   313.8  722.79   323.6  723.21
   372.7   722.9   421.7  723.24     510  725.54   519.8  726.75   529.6  729.93
   539.4  734.29   637.5   780.2   647.3  785.28   657.1  791.05   696.3  815.91
#Mann= 3 , 0 , 0
       0     .08       0   291.1    .045       0   306.1     .06       0
Bank Sta=291.1,306.1
XS Rating Curve= 0 ,0
Exp/Cntr=0.3,0.1

Type RM Length L Ch R = 1 ,40042.3 ,574.5,567.3,560.2
XS GIS Cut Line= 2
     1835164.268      663891.738     1835904.201      663883.867
#Sta/Elev= 30
       0  836.55    19.5  825.85    87.6  785.47   155.8  746.88   165.5  743.63
   175.3  742.41     185  740.24   194.7  736.95   204.5  734.88   253.2  729.16
   301.8  724.25   327.4  719.45     331  718.96   342.4  719.35   399.2  725.31
   428.4  727.11   438.1  729.13   477.1   741.3   496.6  745.47   525.8   749.4
   564.7   752.8   584.2  756.51   603.7  762.98   632.9  774.02   642.6  779.18
   652.4  786.67   662.1  795.64   671.8  803.34   681.6  808.07     740  821.93
#Mann= 3 , 0 , 0
       0     .06       0   327.4    .045       0   342.4     .06       0
Bank Sta=327.4,342.4
XS Rating Curve= 0 ,0
Exp/Cntr=0.3,0.1

Type RM Length L Ch R = 1 ,39475   ,477.8,479.4,480.2
XS GIS Cut Line= 3
     1834976.071       664587.01     1835740.655      664309.927
     1835894.821       664280.76
#Sta/Elev= 30
       0  837.59    19.6   837.7    39.2  836.41      49  834.98    58.8  832.02
   156.8  777.82   176.4  768.37     245  738.82   313.5  729.93   333.1  728.28
   382.1  726.69   450.7  727.36   499.7  726.63   548.7  724.63   558.5  723.49
     572  720.13     587  717.57   587.9  717.47   617.3  719.56   754.4  723.19
   764.2  724.21     774  726.88   813.2  745.19   832.8  755.46   842.7  762.47
   872.1  790.19   881.9  798.24   891.7  803.79   950.5  824.99   970.1  826.74
#Mann= 3 , 0 , 0
       0     .07       0     572    .045       0     587     .06       0
Bank Sta=572,587
XS Rating Curve= 0 ,0
Exp/Cntr=0.3,0.1

Type RM Length L Ch R = 1 ,38995.6 ,575.8,927.6,927.2
XS GIS Cut Line= 4
     1835014.707       665065.53     1835228.155      664891.177
     1835982.321      664676.593     1836203.155       664574.51
#Sta/Elev= 30
       0  840.72      57  827.63   142.6  801.02   152.1  796.97   161.6  791.87
   209.1  764.23   228.1  754.03   247.1  745.13   256.6  741.33   266.1  738.62
   285.4  737.35   314.8  732.45   344.2  729.79   373.6  728.86     403  729.68
   481.4  727.02   540.2  726.24   579.4  723.08   633.6  716.79     648  716.48
   648.6  716.49   775.5  720.75   863.7  729.45   971.5   734.9  1020.5  735.32
  1040.1  737.76  1147.3  764.63  1166.8  770.77  1225.1   801.9    1303  835.74
#Mann= 3 , 0 , 0
       0     .06       0   633.6    .045       0   648.6     .06       0
Bank Sta=633.6,648.6
XS Rating Curve= 0 ,0
Exp/Cntr=0.3,0.1

Type RM Length L Ch R = 1 ,38068   ,1316.3,980.8,990.6
XS GIS Cut Line= 3
     1835051.071      665195.343     1835367.738       665293.26
     1836330.238       664912.01
#Sta/Elev= 30
       0  816.62    29.2  804.52      39  799.51    48.7  792.85      78  768.76
    87.7  761.55    97.5  755.39   107.2  751.24   126.7  748.59   136.5  746.44
   165.7  737.06   185.2  732.28   214.5  727.71   243.7   726.4   321.7  727.24
   438.9  726.08   526.8  723.27   702.6  721.45   897.9  717.12  1015.1  717.32
    1069  716.62  1073.7  716.52    1084  716.74  1093.2  718.36  1122.6  727.08
  1161.6   737.1  1200.7  740.24    1230  745.03  1298.4  759.83  1366.7  777.84
#Mann= 3 , 0 , 0
       0     .06       0    1069    .045       0    1084     .08       0
Bank Sta=1069,1084
XS Rating Curve= 0 ,0
Exp/Cntr=0.3,0.1

Type RM Length L Ch R = 1 ,37087.1 ,147.1,147.2,147.1
XS GIS Cut Line= 3
     1835067.738       665705.76     1835613.571       665518.26
     1836815.655       665530.76
#Sta/Elev= 30
       0  722.26    68.5  719.74   156.5  720.77   185.9  725.29   205.4  726.16
   283.7  724.16   352.2  719.91   401.1  720.15     450  724.04   489.1  720.03
   518.4  718.89   577.1  719.49   606.5  723.29   655.3  725.18   674.9  723.89
   704.2  718.58   899.7   718.1   958.3  713.04   997.4  715.42  1026.5  714.97
  1041.5  714.41  1075.6  717.99  1202.6  720.01  1437.2  718.18  1515.4  724.16
  1622.9  724.87  1642.5     727  1671.8  735.66  1691.3  738.88  1779.3     745
#Mann= 3 , 0 , 0
       0     .06       0  1026.5    .045       0  1041.5     .06       0
Bank Sta=1026.5,1041.5
XS Rating Curve= 0 ,0
Exp/Cntr=0.3,0.1