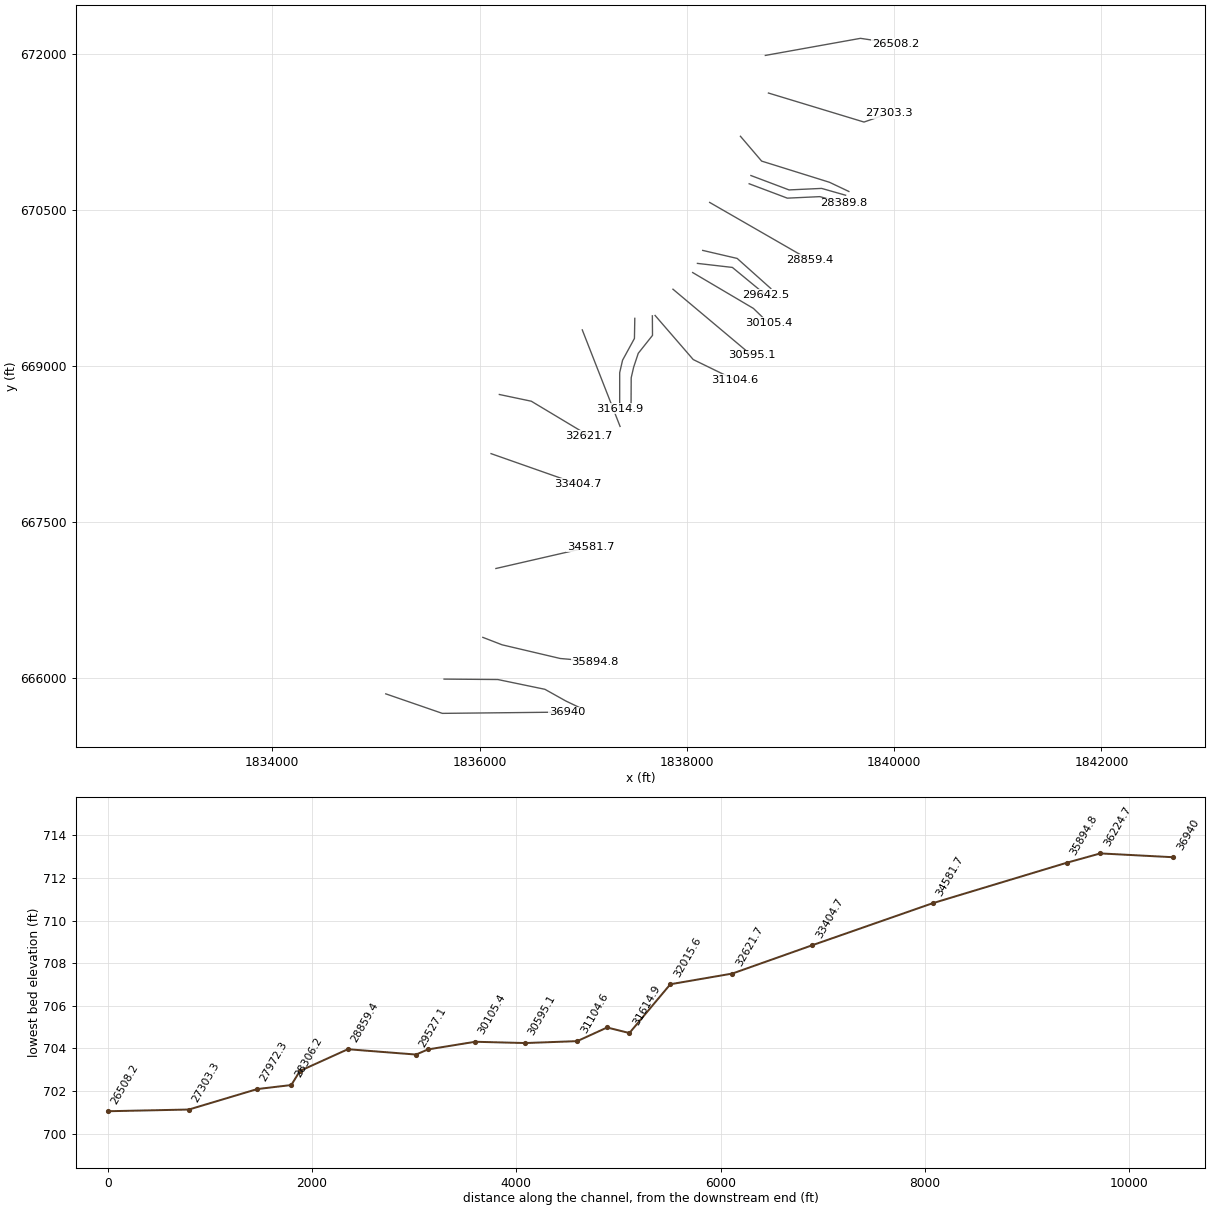
HEC-RAS study MFReedyCrk.prj: MFReedyCrk

--- MFReedyCrk.g01 (geometry) --- (continued)

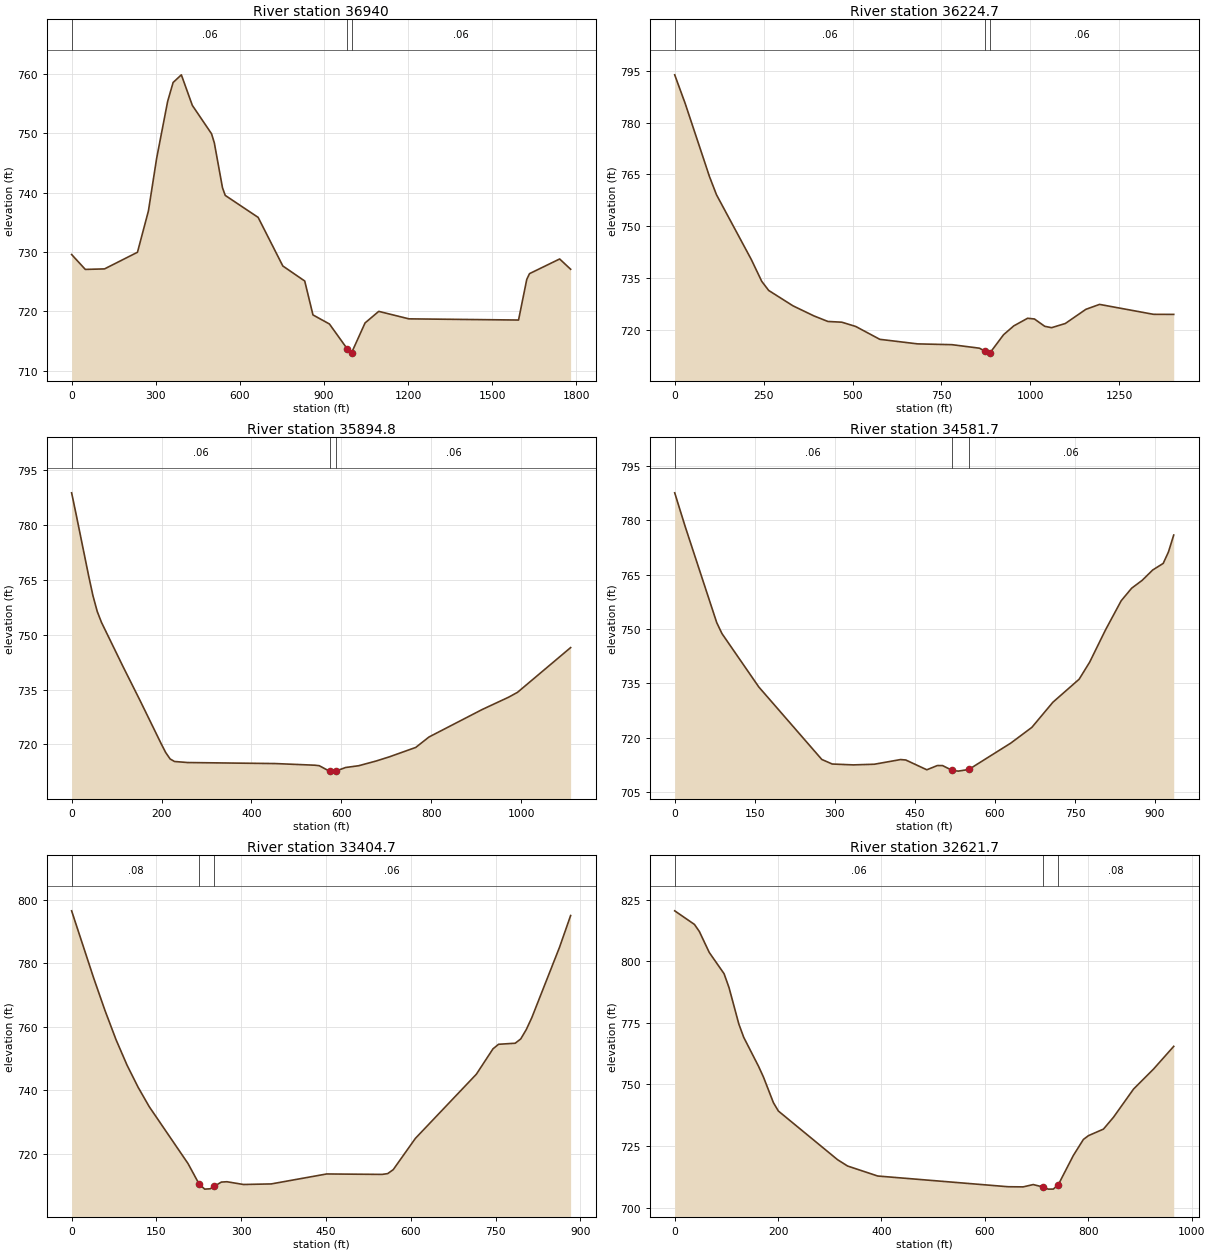
Type RM Length L Ch R = 1 ,36940   ,719.1,715.3,710.3
XS GIS Cut Line= 3
     1835094.821      665851.593     1835640.655      665664.093
     1836842.738      665676.593
#Sta/Elev= 30
       0  729.57    48.9  727.06   117.4  727.15   234.8  729.95   273.9  736.91
   303.2  745.77   342.4  755.34   361.9  758.53   391.3  759.82   430.4  754.68
   498.9   749.9   508.7   748.4     538   740.8   547.8  739.52   665.1  735.82
   753.1  727.64   831.2  725.11   860.6   719.4   919.2  717.88     983  713.68
   997.4  712.97     998     713  1046.3  718.05  1095.1     720  1202.6  718.74
  1593.6  718.54  1622.9  725.38  1632.7  726.35  1740.2  728.82  1779.3  727.09
#Mann= 3 , 0 , 0
       0     .06       0     983    .045       0     998     .06       0
Bank Sta=983,998
XS Rating Curve= 0 ,0
Exp/Cntr=0.3,0.1

Type RM Length L Ch R = 1 ,36224.7 ,330.6,329.9,329.2
XS GIS Cut Line= 5
     1835657.321       665993.26     1836176.071      665989.093
     1836630.238      665895.343     1836832.321      665782.843
     1837003.155      665701.593
#Sta/Elev= 30
       0  793.85    29.4  785.56    97.9   764.3   117.5  759.07   215.3  740.31
   244.7  733.97   264.3  731.32   332.8  726.85   391.5  723.94   430.7  722.33
   469.8  722.12     509  720.88   576.7  717.15     683  715.83   779.6   715.6
   856.9  714.58   871.3  713.77   885.9  713.15   886.3   713.2   924.5  718.48
   953.5  721.06   992.2  723.26  1011.4  723.05  1040.3  720.93  1059.6  720.53
  1098.2  721.74    1156  725.85  1194.5  727.28  1346.2   724.4    1403  724.38
#Mann= 3 , 0 , 0
       0     .06       0   871.3    .045       0   886.3     .06       0
Bank Sta=871.3,886.3
XS Rating Curve= 0 ,0
Exp/Cntr=0.3,0.1

Type RM Length L Ch R = 1 ,35894.8 ,1309.2,1313,1292.5
XS GIS Cut Line= 4
     1836031.433      666393.996     1836217.738      666322.427
     1836778.155      666191.177     1837111.488       666162.01
#Sta/Elev= 30
       0  788.88     9.5  783.31      38  766.09    47.5   760.7      57  756.41
    66.5   753.4     114  741.41   152.1  732.06   199.6  720.11   209.3  717.79
   219.1  716.04   228.8  715.35   258.1  715.06   453.2  714.78     541  714.33
   550.8  714.19   570.3   712.9   574.1  712.83     580  712.71   589.1  712.78
   609.3   713.7   638.6  714.19   677.6  715.49   706.9  716.63   765.4   719.2
   794.8  722.05   912.9  729.56     972  732.95   991.7  734.28  1109.8  746.52
#Mann= 3 , 0 , 0
       0     .06       0   574.1    .045       0   589.1     .06       0
Bank Sta=574.1,589.1
XS Rating Curve= 0 ,0
Exp/Cntr=0.3,0.1

Type RM Length L Ch R = 1 ,34581.7 ,1182.8,1177,1168.5
XS GIS Cut Line= 2
     1836157.475      667055.455     1837068.933      667263.788
#Sta/Elev= 30
       0  787.58    19.7  778.25    78.7  751.79    88.6  748.74   157.5  734.04
   275.6  714.03   295.2  712.77   334.6  712.53     374  712.71   423.2     714
     433  713.88   472.4  711.18   492.1  712.35   501.9  712.34   519.3  711.05
   531.4  710.81   551.1  711.27   629.9  718.56   669.2  722.88   708.6  729.81
   757.8  736.17   777.5  740.87     807  749.71   836.6  757.81   856.2  761.27
   875.9  763.44   895.6  766.29   915.3  768.11   925.1  771.25     935  775.93
#Mann= 3 , 0 , 0
       0     .06       0   519.3    .045       0   551.1     .06       0
Bank Sta=519.3,551.1
XS Rating Curve= 0 ,0
Exp/Cntr=0.3,0.1

Type RM Length L Ch R = 1 ,33404.7 ,787.8,783,778
XS GIS Cut Line= 2
       1836110.6       668158.58     1836943.933      667866.913
#Sta/Elev= 30
       0  796.57    39.2  775.29    58.9  765.23    78.5  755.99    98.1  747.91
   117.7  740.94   137.3  734.84     206  716.89   225.6  710.44   235.4  708.84
   245.2  708.95   251.8  709.68   264.9  711.06   274.7  711.17   304.1   710.3
   353.2  710.48   451.3  713.62   549.4  713.48   559.2  713.73     569  714.97
   608.2  724.83   716.1  745.06   745.6  753.08   755.4   754.5   784.8  754.83
   794.6  756.18   804.4  759.12   814.2  762.88   863.3   785.1   882.9  795.08
#Mann= 3 , 0 , 0
       0     .08       0   225.6    .045       0   251.8     .06       0
Bank Sta=225.6,251.8
XS Rating Curve= 0 ,0
Exp/Cntr=0.3,0.1

Type RM Length L Ch R = 1 ,32621.7 ,625.4,606,584.6
XS GIS Cut Line= 3
     1836190.655      668726.593     1836498.988       668662.01
     1837057.321      668328.677
#Sta/Elev= 30
       0  820.47    38.2  814.95    47.7  812.07    66.8  803.59    95.5  794.94
     105  789.36   124.1  774.49   133.6  769.08   162.3  757.31   171.8  752.94
   190.9  742.62   200.5  739.22     315  719.46   334.4  716.89   392.7  712.83
     645  708.48   674.1  708.42   693.5  709.36   712.9  708.35   722.6  707.51
   732.4  707.53   742.1  709.34   771.2  721.19   790.6  727.68   800.3  729.21
   829.4  731.87   848.8  736.69   887.6  748.13   926.5   756.3   965.3  765.46
#Mann= 3 , 0 , 0
       0     .06       0   712.9    .045       0   742.1     .08       0
Bank Sta=712.9,742.1
XS Rating Curve= 0 ,0
Exp/Cntr=0.3,0.1

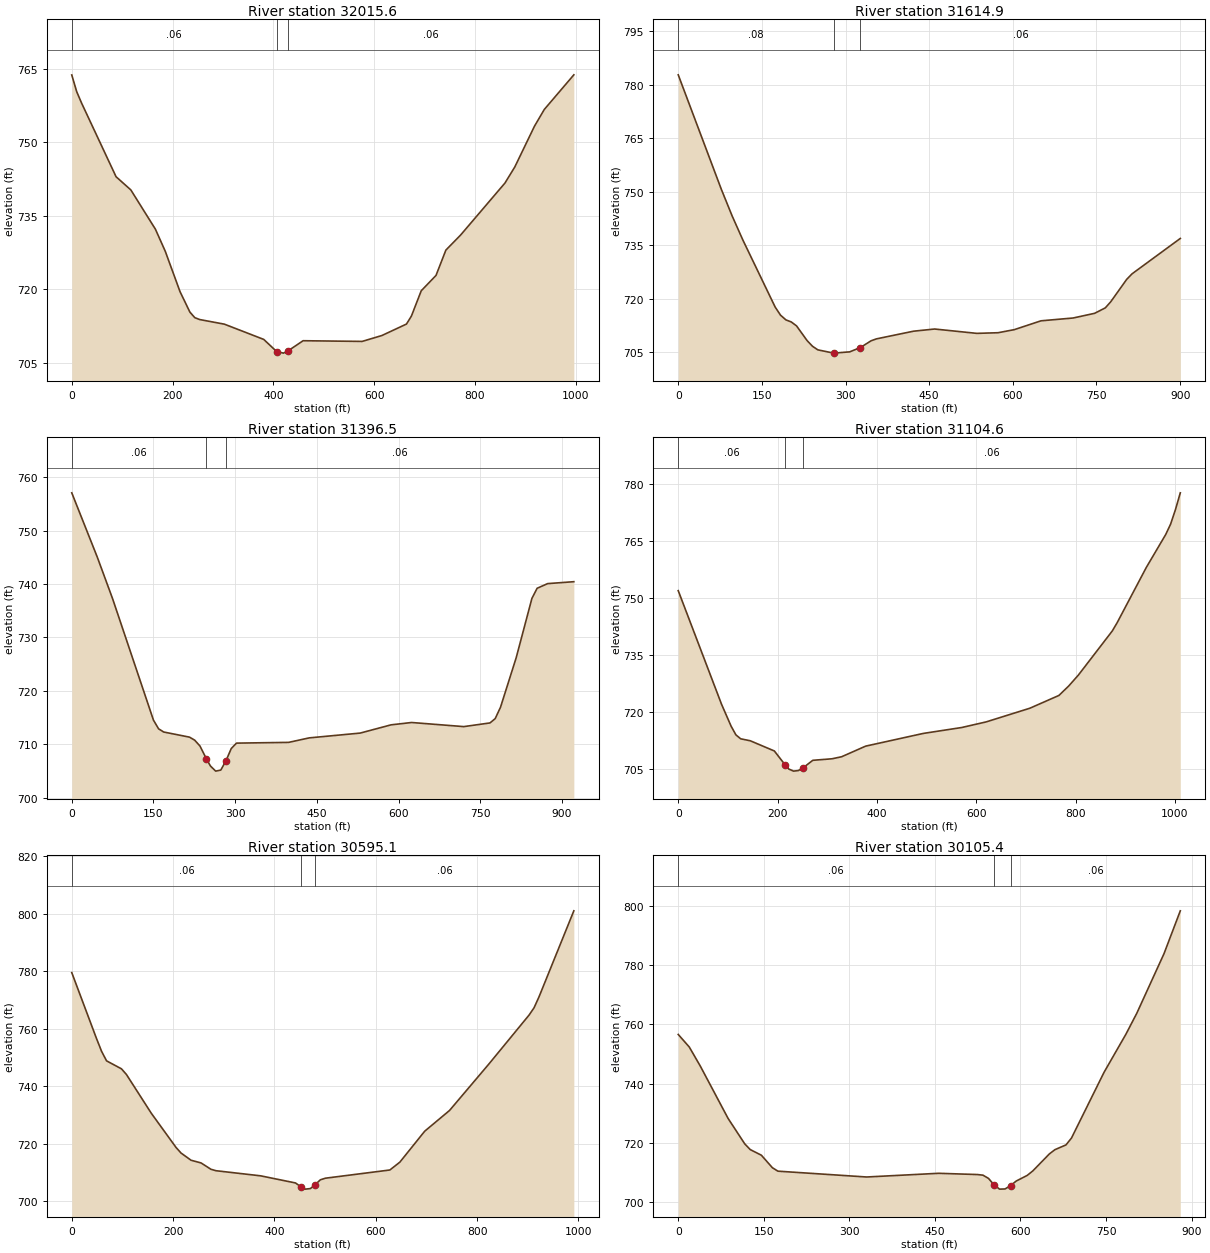
Type RM Length L Ch R = 1 ,32015.6 ,467.7,400.7,376.9
XS GIS Cut Line= 2
     1836990.808      669347.121     1837355.392      668420.038
#Sta/Elev= 30
       0  763.76     9.8  760.35    19.5  758.02    87.9     743   117.2  740.31
     166  732.29   185.6  727.77   214.9  719.53   234.4  715.38   244.2  714.24
   253.9  713.86   302.8  712.92   380.9  709.81   406.6  707.33     420  707.01
   429.7  707.51     459  709.54   576.2   709.4   615.3   710.6   664.1  712.94
   673.9  714.57   693.4  719.73   722.7  722.86   742.3  728.03   771.6  731.11
   859.5  741.71     879  744.98   918.1  753.31   937.6  756.73   996.2  763.79
#Mann= 3 , 0 , 0
       0     .06       0   406.6    .045       0   429.7     .06       0
Bank Sta=406.6,429.7
XS Rating Curve= 0 ,0
Exp/Cntr=0.3,0.1

Type RM Length L Ch R = 1 ,31614.9 ,172.6,218.4,222.2
XS GIS Cut Line= 5
     1837497.599      669457.843     1837494.127      669264.788
     1837379.543       669055.76     1837351.766      668935.968
     1837351.766      668590.135
#Sta/Elev= 30
       0  782.76    77.2  750.69    96.5  743.25   115.8  736.47   173.8  717.64
   183.4  715.37   193.1  714.04   202.6  713.47   212.2  712.35   231.2  708.21
   240.8  706.64   250.3  705.64   278.9  704.72   307.5  705.08   326.6  706.28
   345.6  708.16   355.2  708.71   421.9  710.87   459.8  711.48   535.5  710.26
   573.6  710.44   602.5   711.3   650.5  713.78   708.1  714.57   746.6  715.88
   765.8  717.41   775.4  719.09   804.2  725.41   813.8  726.96   900.3  736.88
#Mann= 3 , 0 , 0
       0     .08       0   278.9    .045       0   326.6     .06       0
Bank Sta=278.9,326.6
XS Rating Curve= 0 ,0
Exp/Cntr=0.3,0.1

Type RM Length L Ch R = 1 ,31396.5 ,259.4,291.9,323.6
XS GIS Cut Line= 6
     1837667.043      669481.802     1837668.432      669294.302
     1837530.932      669122.079     1837486.488      668988.746
     1837462.877      668887.357     1837461.488      668617.913
#Sta/Elev= 30
       0  757.06    46.9  745.02      75  737.24     150  714.53   159.4   712.9
   168.8   712.3   216.2  711.34   225.8  710.77   235.4  709.68   247.4  707.25
   254.6  705.95   264.2  704.98   273.7  705.18   283.3  706.95   292.9  709.21
   302.5  710.22   398.3  710.36     436   711.2   529.7   712.1   586.3  713.64
   624.1  714.08   719.9  713.31     768     714   777.6  714.81   787.3  716.93
   816.1  726.19     845   737.3   854.6   739.2   873.9  740.07     922  740.43
#Mann= 3 , 0 , 0
       0     .06       0   247.4    .045       0   283.3     .06       0
Bank Sta=247.4,283.3
XS Rating Curve= 0 ,0
Exp/Cntr=0.3,0.1

Type RM Length L Ch R = 1 ,31104.6 ,502.7,509.5,516.2
XS GIS Cut Line= 3
     1837693.432      669485.621     1838061.488       669062.01
     1838466.002      668865.829
#Sta/Elev= 30
       0  751.87    87.1  721.98   106.4  716.19   116.1  713.89   125.8  712.85
   145.1  712.33   193.5  709.65   215.9  705.87   222.5   704.9   232.2  704.34
   241.9  704.49   251.6  705.23   270.9  707.19   309.6  707.59     329  708.13
   377.3  710.92   493.4  714.27   570.9  715.83   619.8   717.3   707.8   720.9
   766.4  724.27     786  726.74   805.5  729.62   873.9  741.26   883.7  743.44
   942.3  757.97   981.4  766.65   991.2  769.37    1001   773.2  1010.8  777.63
#Mann= 3 , 0 , 0
       0     .06       0   215.9    .045       0   251.6     .06       0
Bank Sta=215.9,251.6
XS Rating Curve= 0 ,0
Exp/Cntr=0.3,0.1

Type RM Length L Ch R = 1 ,30595.1 ,486.3,489.8,492.6
XS GIS Cut Line= 2
     1837865.808      669737.746     1838626.225       669102.33
#Sta/Elev= 30
       0  779.48    49.1  756.46    58.9  752.11    68.7  748.82    98.1  746.05
   107.9  744.08     157  730.61     206  718.69   215.8  716.77   235.5  714.28
   255.1  713.36   274.7  711.15   284.5  710.65   372.8  708.87   441.5   706.4
   452.8  705.01   461.1  704.25     471  704.44   480.8  705.85   490.6  707.48
   500.4  708.04   627.9   710.9   647.6  713.63   696.6  724.37   745.7  731.59
   824.2  747.91   902.6  764.72   912.5  767.27   922.3  771.08     991  800.95
#Mann= 3 , 0 , 0
       0     .06       0   452.8    .045       0   480.8     .06       0
Bank Sta=452.8,480.8
XS Rating Curve= 0 ,0
Exp/Cntr=0.3,0.1

Type RM Length L Ch R = 1 ,30105.4 ,453.2,462.9,472.5
XS GIS Cut Line= 3
     1838055.901      669897.698     1838642.012      669553.254
     1838786.457      669414.365
#Sta/Elev= 30
       0  756.59    19.4  752.34    38.8  745.86    87.4  728.21   116.5  719.64
   126.2  717.68   145.7  715.78   165.1  711.54   174.8  710.38   330.2  708.41
   456.5  709.66   524.4  709.24   534.2  709.03   543.9  707.94   553.6  705.77
   563.3  704.31     573  704.37   582.7   705.5   592.4  707.03   611.8  708.95
   621.6  710.46   650.7  716.22   660.4  717.65   679.8  719.26   689.4  721.57
   746.6  743.83   784.8  756.66   803.9  763.75   851.6  783.89   880.2  798.38
#Mann= 3 , 0 , 0
       0     .06       0   553.6    .045       0   582.7     .06       0
Bank Sta=553.6,582.7
XS Rating Curve= 0 ,0
Exp/Cntr=0.3,0.1

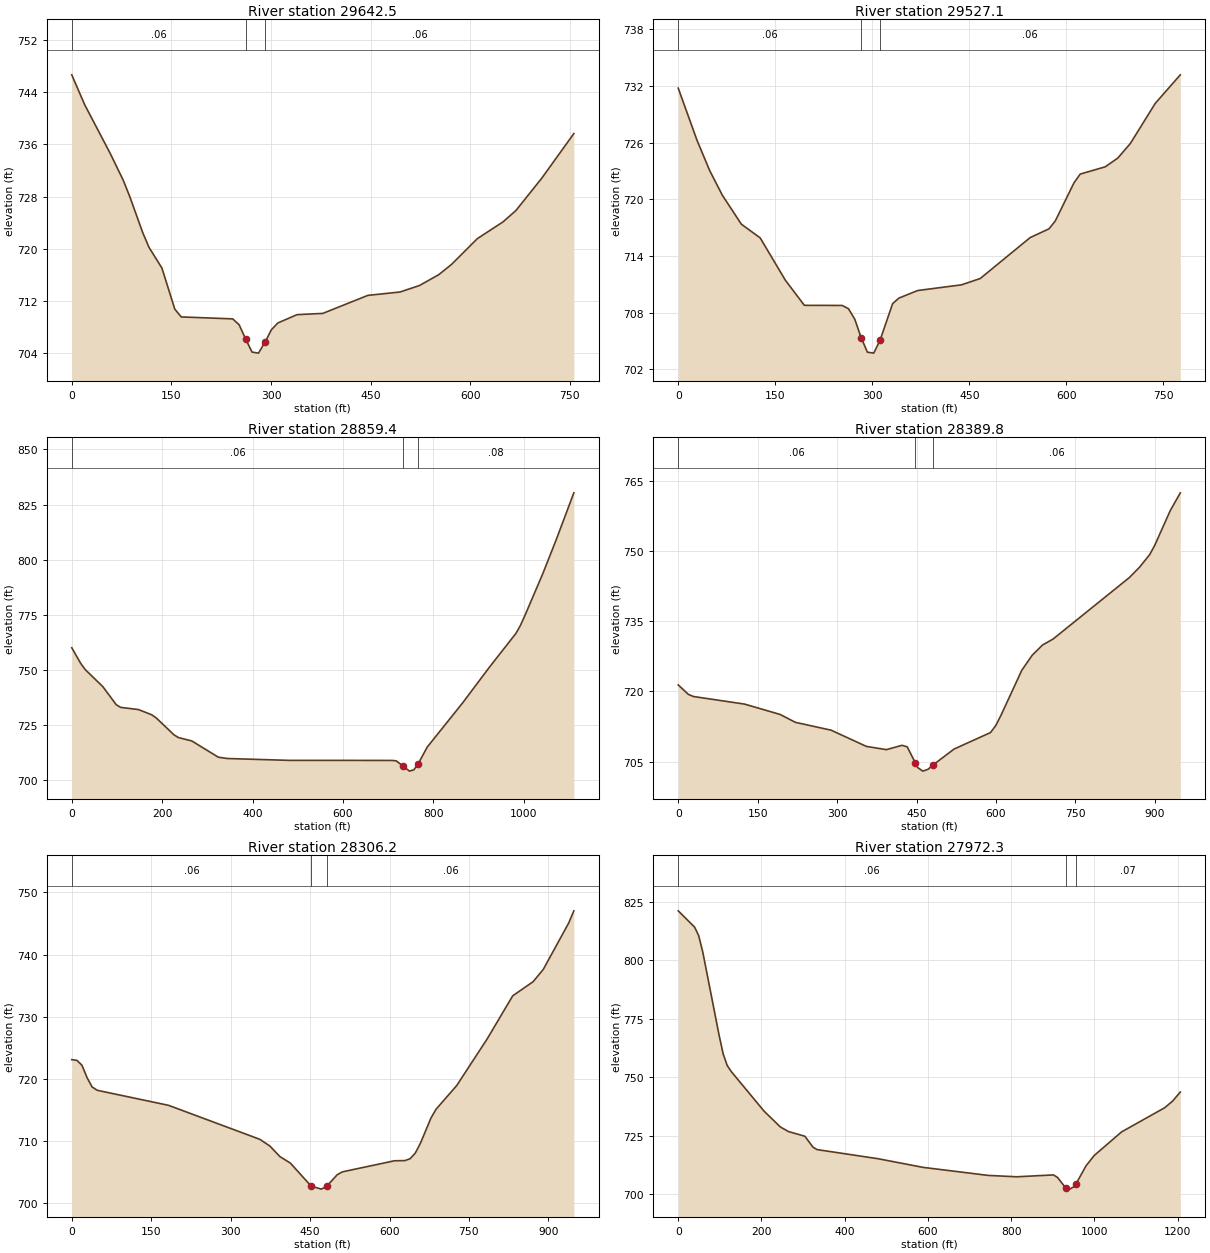
Type RM Length L Ch R = 1 ,29642.5 ,116.8,115.4,112.6
XS GIS Cut Line= 3
     1838102.022      669985.621     1838439.053      669946.908
     1838761.282      669682.749
#Sta/Elev= 30
       0  746.69    19.4  742.11    58.2  734.56    77.5   730.5    87.2  728.03
   106.6  722.52   116.3  720.19   135.7  717.02   155.1  710.71   164.8  709.51
   242.3  709.21     252   708.3   261.7  706.13   271.4  704.11   281.1  703.95
   290.8  705.59   300.5  707.53   310.2  708.58   339.2  709.86     378  710.05
   445.8  712.82   494.3  713.34   523.4  714.33   552.4  715.99   571.8  717.58
   610.6  721.53   649.3  724.11   668.7  725.85   707.5   730.8   755.9  737.67
#Mann= 3 , 0 , 0
       0     .06       0   261.7    .045       0   290.8     .06       0
Bank Sta=261.7,290.8
XS Rating Curve= 0 ,0
Exp/Cntr=0.3,0.1

Type RM Length L Ch R = 1 ,29527.1 ,676.6,667.8,660
XS GIS Cut Line= 3
     1838152.947      670110.318     1838485.309      670033.323
     1838810.242      669744.234
#Sta/Elev= 30
       0  731.77    29.2  726.22    48.7  723.03    68.2  720.43    97.5  717.37
   126.7  715.91   165.7  711.42     195  708.77   253.4  708.76   263.2  708.41
   272.9   707.3   282.7  705.36   292.4  703.81   302.2  703.71   311.9  705.06
   331.4  708.95   341.2  709.54   370.2  710.34   437.8  710.94   466.8  711.61
   544.1  715.95   573.1  716.87   582.8   717.7   611.8  721.75   621.4  722.67
   660.1  723.44   679.4  724.36   698.8   725.9   737.4  730.16   776.1  733.18
#Mann= 3 , 0 , 0
       0     .06       0   282.7    .045       0   311.9     .06       0
Bank Sta=282.7,311.9
XS Rating Curve= 0 ,0
Exp/Cntr=0.3,0.1

Type RM Length L Ch R = 1 ,28859.4 ,455.4,469.6,482.8
XS GIS Cut Line= 2
     1838219.975       670571.08     1839183.517      670018.996
#Sta/Elev= 30
       0  759.98    19.6  752.93    29.5  750.12    68.8  742.29    98.3  734.14
   108.1   732.9   147.4  731.92   176.9  729.53   186.7  728.14     226  720.45
   235.9   719.2   265.3  717.68   324.3  710.28     344  709.69   481.5  708.84
   707.6  708.82   717.4  708.64   732.8  706.27   746.9  703.96   756.7  704.56
   766.5  707.39   786.2  714.87   864.8  735.01   923.8  751.15   982.7  766.57
   992.6  770.22  1002.4  774.67  1041.7  793.54  1071.2  808.85  1110.5  830.31
#Mann= 3 , 0 , 0
       0     .06       0   732.8    .045       0   766.5     .08       0
Bank Sta=732.8,766.5
XS Rating Curve= 0 ,0
Exp/Cntr=0.3,0.1

Type RM Length L Ch R = 1 ,28389.8 ,84,83.6,287.1
XS GIS Cut Line= 5
     1838601.083      670750.392     1838880.395       670645.65
     1838969.134      670612.191      1839283.36      670626.739
     1839514.665      670561.275
#Sta/Elev= 30
       0  721.41    19.2  719.37    28.9  718.92   125.1   717.3   192.4  715.08
   221.3  713.39   288.7  711.71   355.2  708.24   393.1  707.54   422.6  708.47
   432.5  708.13   447.7  704.72   452.1  703.71     462  702.94   471.8  703.34
   481.6   704.3   520.9  707.67   589.7   711.2   599.6   712.7   609.4  714.88
   648.7  724.53   668.4  727.76     688  729.96   707.7  731.22   851.9   744.4
   871.2  746.63   890.4  749.34     900  751.35   928.9  758.69   948.1  762.55
#Mann= 3 , 0 , 0
       0     .06       0   447.7    .045       0   481.6     .06       0
Bank Sta=447.7,481.6
XS Rating Curve= 0 ,0
Exp/Cntr=0.3,0.1

Type RM Length L Ch R = 1 ,28306.2 ,339.9,333.9,123.8
XS GIS Cut Line= 5
     1838617.837      670829.435     1838897.149      670724.693
     1838985.888      670691.234     1839300.114      670705.782
     1839531.419      670640.318
#Sta/Elev= 30
       0  723.11     9.6     723    19.2  722.22    28.9  720.21    38.5  718.71
    48.1  718.18   182.8  715.76   355.2  710.29   374.2  709.21   393.1  707.51
   412.8  706.47   452.1  702.76   471.4  702.28   481.6  702.76   501.3   704.6
   511.1  705.06   609.4  706.84   629.1  706.87   638.9  707.17   648.7  708.08
   658.6   709.7   678.2   713.7     688  715.14   726.9  718.94   784.6  726.47
   832.7  733.38   871.2  735.65   890.4  737.63   938.5  745.11   948.1  747.05
#Mann= 3 , 0 , 0
       0     .06       0   452.1    .045       0   481.6     .06       0
Bank Sta=452.1,481.6
XS Rating Curve= 0 ,0
Exp/Cntr=0.3,0.1

Type RM Length L Ch R = 1 ,27972.3 ,669.7,668.9,668.3
XS GIS Cut Line= 4
      1838516.85      671206.496     1838721.379      670968.066
     1839375.786      670764.669     1839563.046      670676.399
#Sta/Elev= 30
       0  821.27    39.3   814.3    49.1  810.66    58.9  803.69    98.2     768
     108  759.97   117.8     755   127.6   752.4   206.2   735.5   245.4  728.71
     265  726.74   304.3  724.74   323.9  720.04   333.7  719.02   480.6   715.1
   588.2  711.41   744.9  707.96   813.4  707.37   901.5  708.18   911.3  707.12
   930.9  702.63   940.7  702.09   950.5  703.08   956.3   704.5   979.8  712.05
   999.4  716.47  1065.3   726.6  1168.8  736.94  1187.6  739.74  1206.4  743.66
#Mann= 3 , 0 , 0
       0     .06       0   930.9    .045       0   956.3     .07       0
Bank Sta=930.9,956.3
XS Rating Curve= 0 ,0
Exp/Cntr=0.3,0.1

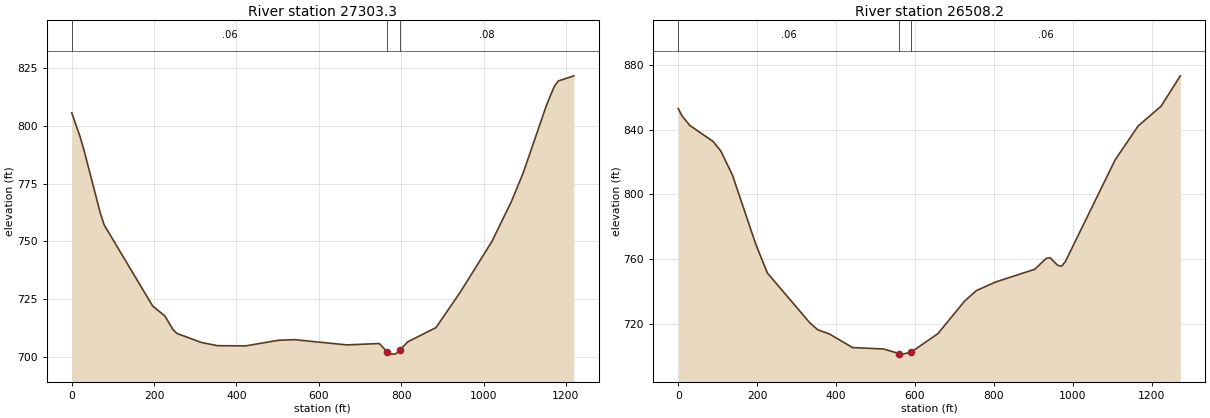
Type RM Length L Ch R = 1 ,27303.3 ,802.9,795.1,802.8
XS GIS Cut Line= 3
     1838787.177      671621.741     1839709.052      671343.095
     1839951.239      671426.428
#Sta/Elev= 30
       0  805.65    19.6  795.67    29.5  789.61    68.8  762.61    78.6  757.14
   196.5  721.96     226  717.69   245.7   711.8   255.5  710.09   314.5  706.19
   353.8  704.79   422.6  704.71   501.2  707.12   540.5   707.4   668.2  705.13
   746.9  705.73   766.5  702.01   776.4  701.13   786.2  701.18     796  702.73
   815.7  706.44   884.4  712.62   943.4  727.98    1020  749.88  1067.4   767.2
  1095.9   779.5  1152.8     809  1171.8  817.17  1181.2  819.48  1219.2  821.73
#Mann= 3 , 0 , 0
       0     .06       0   766.5    .045       0     796     .08       0
Bank Sta=766.5,796
XS Rating Curve= 0 ,0
Exp/Cntr=0.3,0.1

Type RM Length L Ch R = 1 ,26508.2 ,1243.2,1263.5,1267.7
XS GIS Cut Line= 3
     1838757.301      671982.972      1839675.27      672147.035
     1840011.208      672096.253
#Sta/Elev= 30
       0  853.13     9.8  848.55    29.4  842.67    88.3  832.76     108   826.8
   137.4   811.9   196.3  769.27   225.8  751.33   333.7  720.35   353.4  716.17
   382.8  713.58   441.7  705.12   520.2  704.23   559.5   701.4   569.3  701.05
   590.5  702.34   657.7  713.65   726.4  734.09   755.8  740.43   804.9  745.78
   903.1  753.55   932.5  760.33   942.2  760.78   961.6  756.03   971.3  755.46
     981  758.34  1107.2  821.37  1165.5  842.36  1223.7  854.61  1272.3   873.4
#Mann= 3 , 0 , 0
       0     .06       0   559.5    .045       0   590.5     .06       0
Bank Sta=559.5,590.5
XS Rating Curve= 0 ,0
Exp/Cntr=0.3,0.1