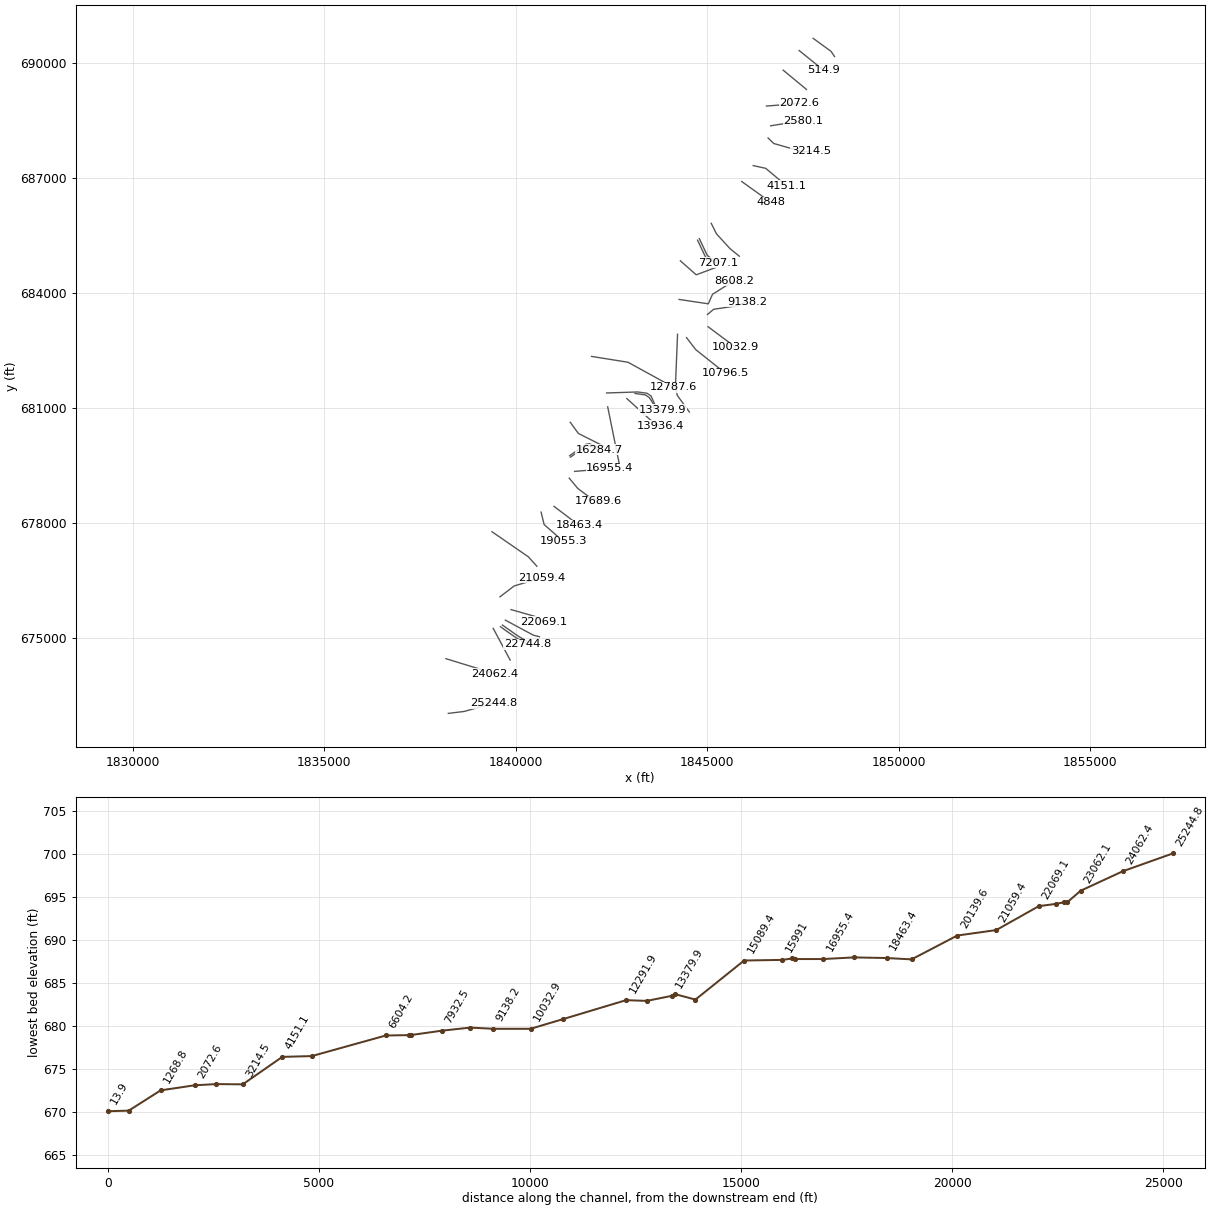
HEC-RAS study MFReedyCrk.prj: MFReedyCrk

--- MFReedyCrk.g01 (geometry) --- (continued)

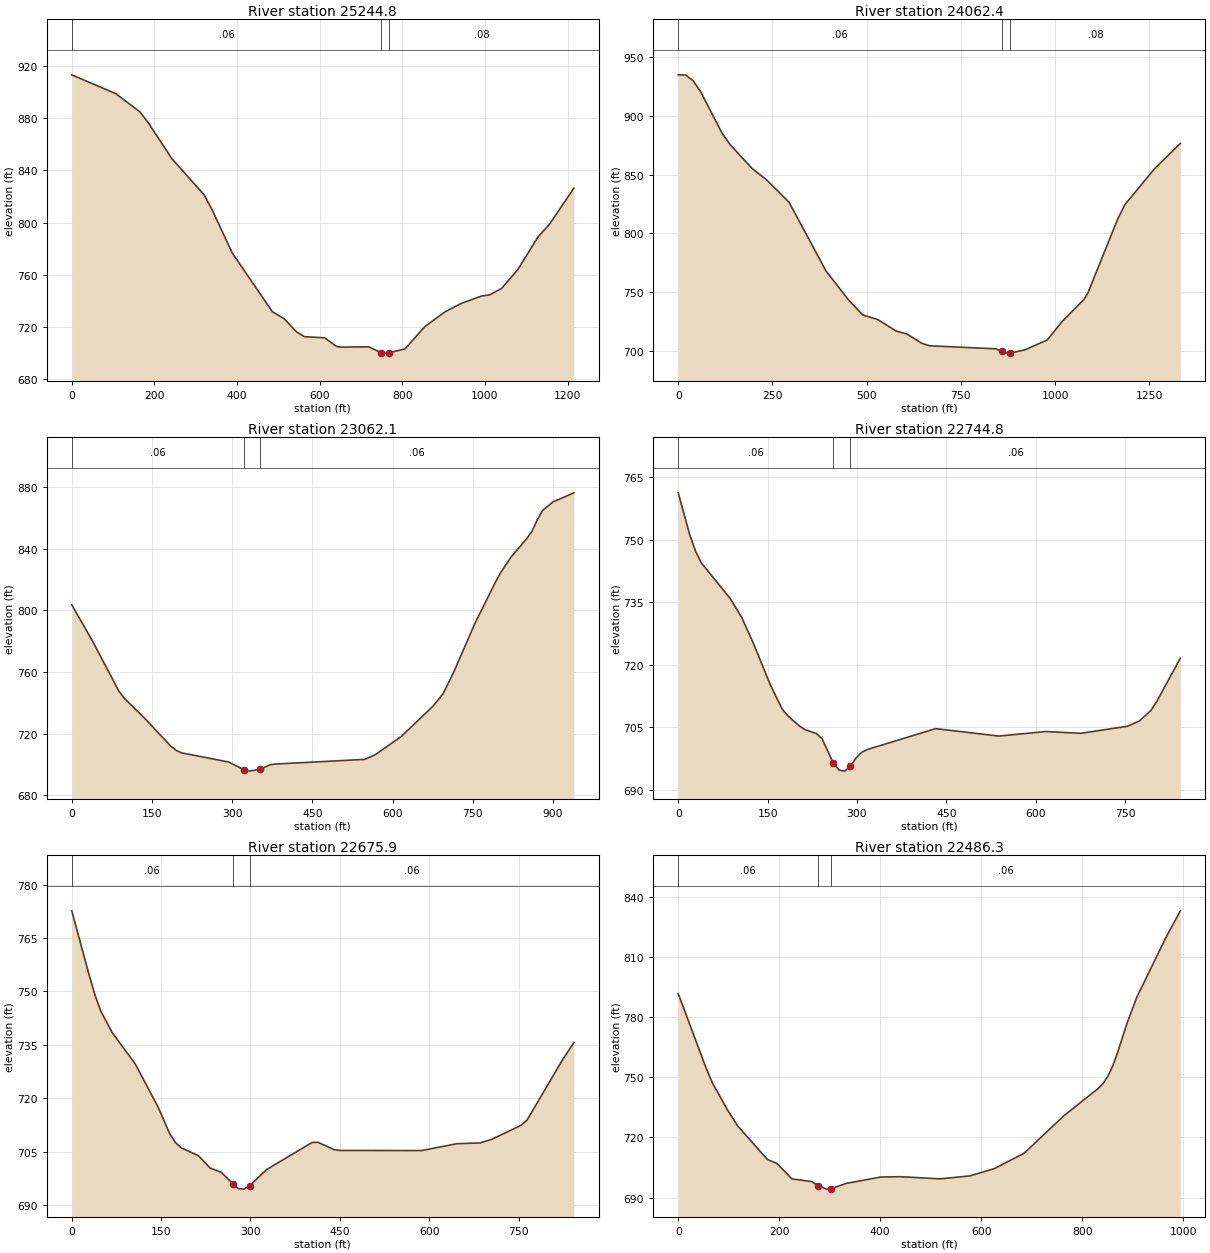
Type RM Length L Ch R = 1 ,25244.8 ,1195.3,1182.4,1167.1
XS GIS Cut Line= 3
     1838240.808      673034.621      1838655.08      673084.826
       1839423.1      673300.246
#Sta/Elev= 30
       0  913.26   106.8  898.77     165  884.91   184.4  876.84   242.6  848.91
   320.3  821.36   339.7  809.89   388.2  776.91   485.4  731.84   514.6  726.31
   543.8  716.43   563.2   712.7   611.8  711.87     641  705.23   650.8  704.74
   718.9  704.94     748  700.49   757.8  700.12   767.5  700.37   806.4  703.35
     855  720.57   903.7  731.82   942.6   738.2   991.2   743.8  1010.7  744.67
  1039.9  749.61  1078.8  763.81  1127.4  788.67  1156.6  799.04    1215  826.43
#Mann= 3 , 0 , 0
       0     .06       0     748    .045       0   767.5     .08       0
Bank Sta=748,767.5
XS Rating Curve= 0 ,0
Exp/Cntr=0.3,0.1

Type RM Length L Ch R = 1 ,24062.4 ,1016.3,1000.3,981.9
XS GIS Cut Line= 2
     1838178.308      674461.705     1839451.956      674070.562
#Sta/Elev= 30
       0  934.95    19.6  934.79    39.2  929.99    58.8  920.95   117.6  884.54
   137.2  875.77   195.9  855.27   235.1  845.36   293.9  826.58   391.9  768.11
   450.6  743.86   489.8  730.49     529  726.72     578  716.91   607.4  714.25
   646.6   706.4   666.2  704.33   842.5  701.72   859.1  699.63   871.9  698.05
   881.7  698.08   920.9  700.91   979.7  709.35  1018.9  725.01  1077.6  744.15
  1087.4  749.46  1165.8  811.81  1185.4  824.48  1263.8  854.95  1332.4  876.59
#Mann= 3 , 0 , 0
       0     .06       0   859.1    .045       0   881.7     .08       0
Bank Sta=859.1,881.7
XS Rating Curve= 0 ,0
Exp/Cntr=0.3,0.1

Type RM Length L Ch R = 1 ,23062.1 ,306.6,317.3,328.5
XS GIS Cut Line= 2
     1839412.683      675253.371     1839855.392      674425.246
#Sta/Elev= 30
       0  803.65    39.1  779.94      88  747.71    97.8  743.21   136.9  729.83
   185.8   711.8   195.6  709.15   205.4  707.63   293.4  701.69   322.8  696.59
   332.6  695.78   352.1  697.01   371.7     700   381.5  700.38   547.8   703.4
   567.3  706.37   616.2  718.26   674.9  737.64   694.5  745.94   714.1  759.77
   753.2  790.95   792.3  818.28   802.1  824.52   821.6  834.62     851  846.55
   860.8  851.39   870.6  858.74   880.3  864.74   899.9  870.32     939  876.24
#Mann= 3 , 0 , 0
       0     .06       0   322.8    .045       0   352.1     .06       0
Bank Sta=322.8,352.1
XS Rating Curve= 0 ,0
Exp/Cntr=0.3,0.1

Type RM Length L Ch R = 1 ,22744.8 ,68.7,68.9,68.7
XS GIS Cut Line= 4
     1839602.188      675294.581     1839775.925      675171.349
     1840010.268      675007.712     1840307.238      674833.975
#Sta/Elev= 30
       0  761.21    19.4   751.1      29  747.24    38.7  744.42    87.1  735.88
   106.5  731.34   125.9   725.2   154.9  715.06   174.3  709.38     184   707.7
   203.3  705.28     213  704.39   232.1  703.45   241.6  702.19   260.6   696.3
   270.2  694.68   279.7  694.44   289.2  695.66   298.8  697.64   308.3  698.98
   317.8  699.64   432.1  704.63   538.2  702.85   616.8  703.94   675.8  703.51
   754.4  705.21   774.1  706.48   793.7  709.02   803.6   711.2   842.9  721.53
#Mann= 3 , 0 , 0
       0     .06       0   260.6    .045       0   289.2     .06       0
Bank Sta=260.6,289.2
XS Rating Curve= 0 ,0
Exp/Cntr=0.3,0.1

Type RM Length L Ch R = 1 ,22675.9 ,187.1,189.6,192
XS GIS Cut Line= 4
     1839652.693      675339.025      1839826.43      675215.793
     1840060.773      675052.157     1840357.743      674878.419
#Sta/Elev= 30
       0  772.67      29  754.75    38.7  749.15    48.4  744.58    67.8  738.46
   106.5  729.65   145.2  717.41   164.6  709.96   174.3   707.5     184  706.04
     213  703.79   232.1  700.39   251.1  699.16   270.2  695.97   279.7  694.58
   289.2  694.44   298.8  695.43   327.3  699.96   403.6  707.56   413.1  707.61
   441.7  705.45   451.2  705.32   587.3  705.28   646.3   707.2   685.6  707.43
   705.3  708.46   754.4  712.39   764.2  713.81   823.2  730.59   842.9  735.61
#Mann= 3 , 0 , 0
       0     .06       0   270.2    .045       0   298.8     .06       0
Bank Sta=270.2,298.8
XS Rating Curve= 0 ,0
Exp/Cntr=0.3,0.1

Type RM Length L Ch R = 1 ,22486.3 ,412.1,417.2,422
XS GIS Cut Line= 3
     1839730.392      675466.913     1840463.387      675073.717
     1840621.017      675034.621
#Sta/Elev= 30
       0  791.67    48.9  758.75    58.7  752.35    68.5  746.83    97.9  733.58
   117.4  725.85   176.2  709.11   195.7  706.97   225.1  699.34   264.2  698.03
   276.8  696.03   293.6  694.25   303.4  694.52   332.7   697.1   401.2  700.28
   440.4  700.44   518.6  699.37   577.4  700.84   626.3   704.5     685  712.15
   763.3  730.74   831.8  744.44   841.4  746.92   850.9  750.56   860.5  755.67
     870  762.26   889.1   777.2   908.2  789.94   965.5   819.5   994.2  832.92
#Mann= 3 , 0 , 0
       0     .06       0   276.8    .045       0   303.4     .06       0
Bank Sta=276.8,303.4
XS Rating Curve= 0 ,0
Exp/Cntr=0.3,0.1

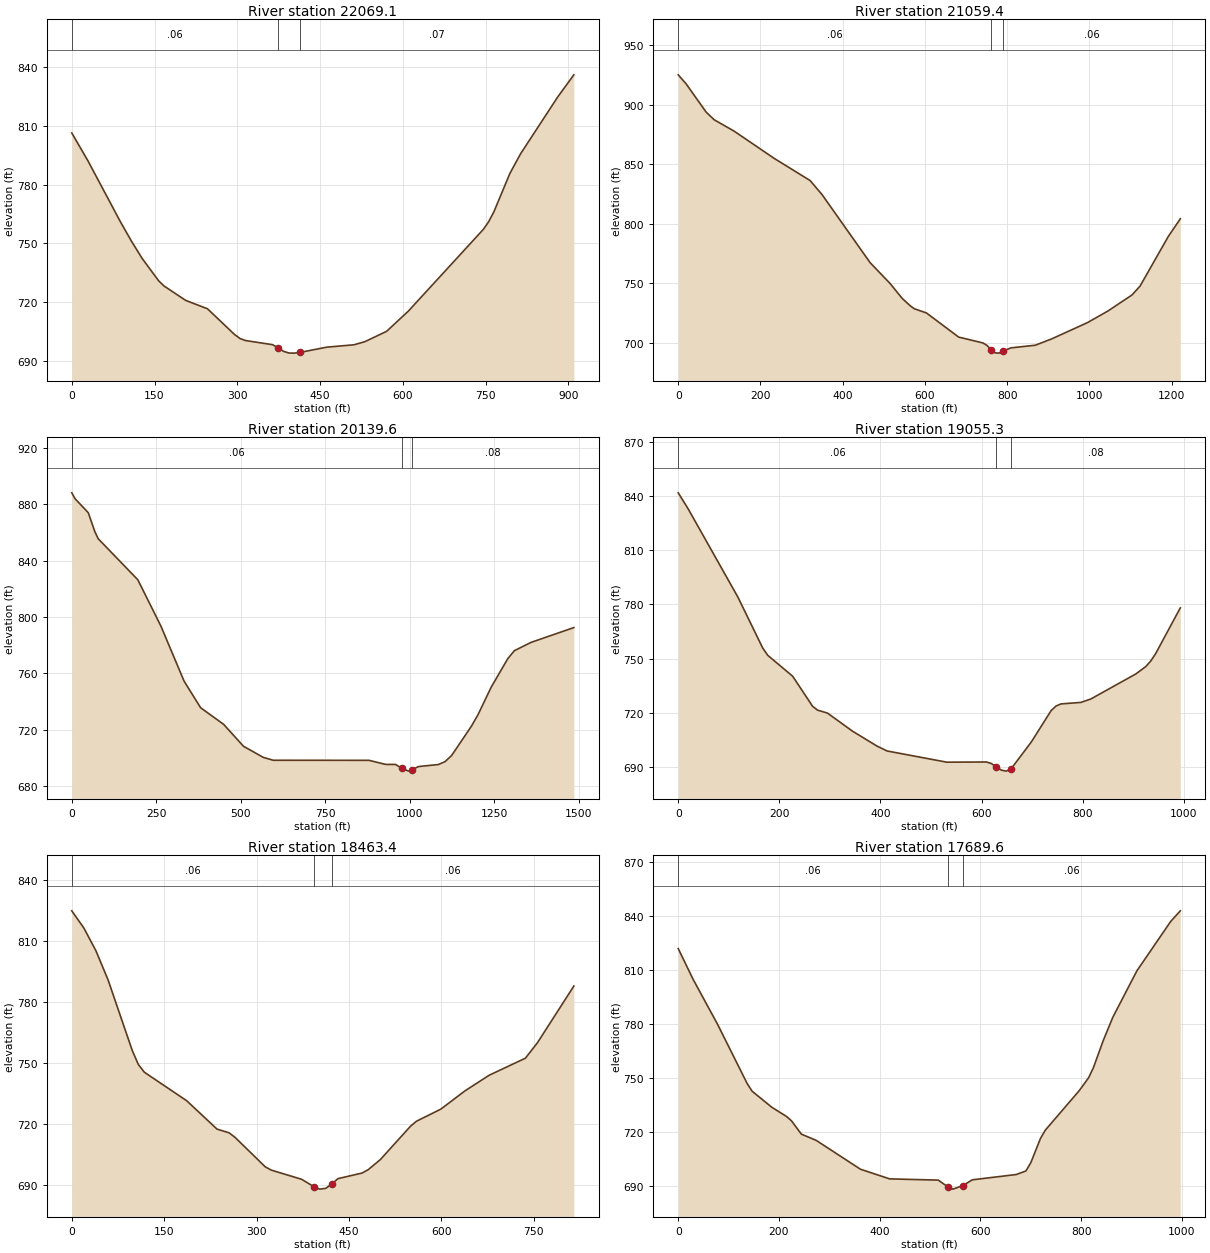
Type RM Length L Ch R = 1 ,22069.1 ,995.8,1009.7,1023.3
XS GIS Cut Line= 3
     1839876.935      675743.066     1840501.177      675565.288
     1840721.379      675425.894
#Sta/Elev= 30
       0  806.45    29.5  792.13    88.5  760.89   108.2  751.16   127.8  742.23
   157.4  730.95   167.2  728.27   206.5   720.9   245.9  716.64     295  703.48
   304.9  701.44   314.7  700.42   363.9  698.29   373.7  696.73   383.5  694.92
   393.4  694.03   403.2  693.98     413  694.32   462.2  697.03   511.4  698.24
     531  699.82   570.4   705.1   609.7   715.4   745.6  757.16   755.2  761.04
   764.9  766.21   793.8  785.76   813.2  795.82   880.7  824.93   909.7  836.15
#Mann= 3 , 0 , 0
       0     .06       0   373.7    .045       0     413     .07       0
Bank Sta=373.7,413
XS Rating Curve= 0 ,0
Exp/Cntr=0.3,0.1

Type RM Length L Ch R = 1 ,21059.4 ,940,919.8,898.9
XS GIS Cut Line= 3
     1839589.767      676076.288     1839960.448      676359.776
     1840683.517      676576.288
#Sta/Elev= 30
       0  925.04    19.4  917.35      68  893.66    87.5  887.28   136.1  877.69
   233.3  854.86   320.8  836.22     350  824.34   466.7  767.25   515.7  749.57
   545.1  737.07   564.7  730.86   574.5  728.45   603.9  724.93   682.3  704.65
   741.1  699.77   750.9  697.76   760.7   694.2   770.5  691.41   780.3  691.19
   790.1  692.96   809.7  695.61   868.6  697.83   907.8  703.04     996   716.9
    1045  726.52  1103.8  740.03  1123.4  747.48    1192   789.1  1221.4  804.09
#Mann= 3 , 0 , 0
       0     .06       0   760.7    .045       0   790.1     .06       0
Bank Sta=760.7,790.1
XS Rating Curve= 0 ,0
Exp/Cntr=0.3,0.1

Type RM Length L Ch R = 1 ,20139.6 ,1086.1,1084.3,1081.4
XS GIS Cut Line= 3
     1839381.433      677774.205     1840330.595       677119.76
     1840553.308      676873.163
#Sta/Elev= 30
       0  888.25     9.8  884.04    48.8  874.14    68.4  860.61    78.2  855.64
   195.4  826.49   263.8  793.54   332.2  754.52     381  735.64   449.4  723.76
   508.1  708.19   566.7  700.32     596  698.28   879.3  698.24   928.2  695.34
   957.5  695.33     977  692.52   996.6  690.56  1006.4  691.53  1025.9  693.81
  1084.5  695.25  1104.1  697.29  1123.6  701.62  1182.2   722.5  1201.8   730.7
  1240.9  750.28  1289.7  770.42  1309.3  776.12  1358.1  781.96  1485.2  792.53
#Mann= 3 , 0 , 0
       0     .06       0     977    .045       0  1006.4     .08       0
Bank Sta=977,1006.4
XS Rating Curve= 0 ,0
Exp/Cntr=0.3,0.1

Type RM Length L Ch R = 1 ,19055.3 ,589.8,591.9,593.5
XS GIS Cut Line= 3
     1840663.299      678286.185     1840742.465      677961.185
     1841238.299      677527.851
#Sta/Elev= 30
       0  841.64    19.7  832.75   118.1  783.94   167.2  755.78   177.1  751.79
   226.3  740.25   265.6  723.68   275.5   721.5   295.2  719.87   344.3  709.94
   393.5  701.57   413.1  698.92   531.1  692.73   609.7  692.83   619.5  691.96
   629.4  690.01   639.2  688.31     649  687.78   658.8  689.22   698.2  703.85
   737.5  721.24   747.3  723.78   757.1  724.94   796.4  725.77   816.1  727.67
   904.6  741.44   924.2  745.46     934  748.46   943.9  752.57     993  778.05
#Mann= 3 , 0 , 0
       0     .06       0   629.4    .045       0   658.8     .08       0
Bank Sta=629.4,658.8
XS Rating Curve= 0 ,0
Exp/Cntr=0.3,0.1

Type RM Length L Ch R = 1 ,18463.4 ,773.3,773.9,774.4
XS GIS Cut Line= 2
     1841000.799      678436.185     1841650.799      677944.518
#Sta/Elev= 30
       0   824.9    19.6  816.46    39.3   805.2    58.9  790.94    98.2  756.16
     108  749.32   117.8  745.48   186.6  731.43   235.7  717.49   255.3  715.66
   265.1   713.4   314.2  698.88     324  697.28   373.1  692.78   393.6  689.04
   402.6  687.94   412.4  688.34   422.2   690.5     432  693.09   471.3  695.86
   481.2  697.51   500.8  702.45   549.9  718.91   559.7  721.38     599  727.29
   638.3  736.31   677.5  743.98   736.4  752.38   756.1  760.07     815  787.87
#Mann= 3 , 0 , 0
       0     .06       0   393.6    .045       0   422.2     .06       0
Bank Sta=393.6,422.2
XS Rating Curve= 0 ,0
Exp/Cntr=0.3,0.1

Type RM Length L Ch R = 1 ,17689.6 ,717.9,734.2,749.3
XS GIS Cut Line= 4
     1841396.632      679173.685     1841621.632      678902.851
     1841909.132      678690.351     1842171.632      678573.685
#Sta/Elev= 30
       0  822.03    29.3  805.01    78.2  779.78   136.9   746.8   146.7  742.55
   185.8  733.62   215.2  728.45     225  726.02   244.5  718.64   273.9  715.18
   361.8   699.1   419.7  693.72   516.4  693.03   535.7  689.18   545.4  688.01
   564.7  689.93     584   693.2     671  696.14   690.3  698.12     700  702.69
   719.2   716.2   728.8  720.85   795.8  742.73   814.9  750.08   824.5  755.77
   843.7  770.64   862.8  783.69   910.7  809.61   977.7  837.08   996.9  843.04
#Mann= 3 , 0 , 0
       0     .06       0   535.7    .045       0   564.7     .06       0
Bank Sta=535.7,564.7
XS Rating Curve= 0 ,0
Exp/Cntr=0.3,0.1

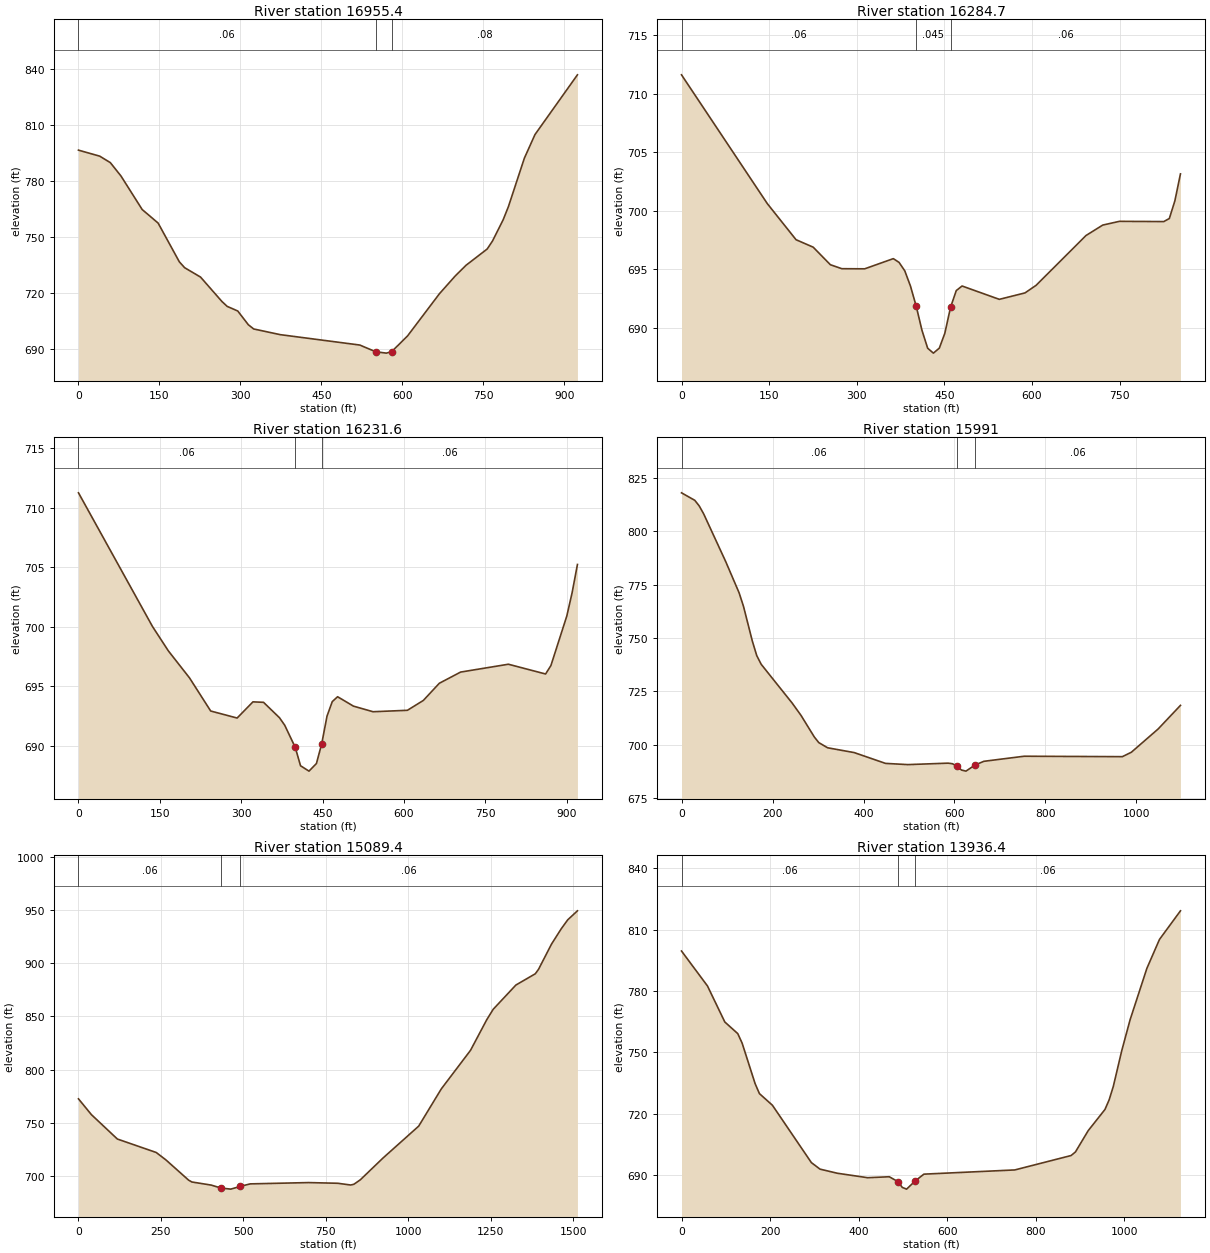
Type RM Length L Ch R = 1 ,16955.4 ,658.6,670.7,681.5
XS GIS Cut Line= 2
     1841538.299      679348.685     1842459.132      679427.851
#Sta/Elev= 30
       0  796.54    39.3  793.32      59  789.85    78.7  782.69     118  764.73
   147.5  757.48   186.8  736.73   196.6  733.58   226.1  728.55   265.5  715.54
   275.3  712.88     295  710.38   314.6  703.03   324.5  700.76   373.6  697.72
   521.1  692.15   550.6  688.54   570.3  687.82   580.1  688.61   609.6  697.06
   668.6  719.64   698.1  729.23   717.8  734.86   757.1  743.61   766.9  747.89
   786.6  759.23   796.4  766.33   825.9  792.24   845.6  804.91   924.2  836.88
#Mann= 3 , 0 , 0
       0     .06       0   550.6    .045       0   580.1     .08       0
Bank Sta=550.6,580.1
XS Rating Curve= 0 ,0
Exp/Cntr=0.3,0.1

Type RM Length L Ch R = 1 ,16284.7 ,51.1,53.1,61.4
XS GIS Cut Line= 4
     1841429.008      679721.709     1841849.942      680009.222
     1841917.593      680022.376      1842173.16      679919.022
#Sta/Elev= 30
       0  711.62     147   700.6   196.1  697.52   225.5  696.88   254.9  695.38
   274.5  695.04   313.7  695.03   362.7   695.9   372.5  695.58   382.3  694.86
   392.1  693.55   401.9  691.83   411.7  689.78   421.5  688.24   431.3  687.82
   441.5  688.25   450.9  689.52   460.7  691.74   470.5  693.17   480.4  693.56
   544.2  692.42   588.2  692.97   607.2  693.62   692.7  697.88   721.3  698.77
   749.8  699.09   825.8  699.07   835.3  699.33   844.8  700.84   854.4  703.15
#Mann= 3 , 0 , 0
       0     .06       0   401.9    .045       0   460.7     .06       0
Bank Sta=401.9,460.7
XS Rating Curve= 0 ,0
Exp/Cntr=0.3,0.1

Type RM Length L Ch R = 1 ,16231.6 ,267.5,240.6,208.3
XS GIS Cut Line= 4
     1841410.216      679759.292     1841823.634      680052.443
     1841921.351      680071.235     1842214.502      679960.364
#Sta/Elev= 30
       0  711.27   136.4  700.04   165.7  697.99   204.7  695.72   243.7  692.94
   292.4  692.35   321.6  693.71   341.1  693.67   370.4  692.38   380.1  691.75
   399.6  689.88   409.3  688.34   424.9  687.89   438.6  688.53   448.3  690.18
   458.1  692.51   467.8  693.73   477.6  694.14   506.8  693.35     543  692.88
   606.3     693   635.7  693.83   665.1  695.27   704.3  696.21   792.4  696.87
     861  696.05   870.8  696.76   900.1  700.92   909.9  702.88   919.7  705.25
#Mann= 3 , 0 , 0
       0     .06       0   399.6    .045       0   448.3     .06       0
Bank Sta=399.6,448.3
XS Rating Curve= 0 ,0
Exp/Cntr=0.3,0.1

Type RM Length L Ch R = 1 ,15991   ,912.6,901.6,891.4
XS GIS Cut Line= 3
     1841424.369      680631.052      1841635.48      680339.385
     1842293.813       680008.83
#Sta/Elev= 30
       0  817.99    29.2  814.48    38.9  811.86    48.7  808.14    97.3  785.73
   126.5  771.23   136.2  764.88   155.7  748.57   165.4  741.76   175.2  737.71
   243.3  719.55   262.7   713.8   291.9  703.71   301.7  701.07   321.1  698.65
   379.7  696.39   448.4  691.34   497.6  690.77     586  691.45   595.8  691.17
   605.6  689.94   615.4  688.23   625.2  687.72   644.9  690.54   664.5  692.31
   752.9  694.69     969  694.49   988.7  696.55  1047.6  707.44  1096.7   718.5
#Mann= 3 , 0 , 0
       0     .06       0   605.6    .045       0   644.9     .06       0
Bank Sta=605.6,644.9
XS Rating Curve= 0 ,0
Exp/Cntr=0.3,0.1

Type RM Length L Ch R = 1 ,15089.4 ,1147.5,1153,1157
XS GIS Cut Line= 2
     1842401.833      681033.753     1842703.413      679550.713
#Sta/Elev= 30
       0  772.54    39.3  757.66   117.9  734.76   235.8   722.1   265.3   715.1
   334.1  696.08     344  694.36   402.9  691.42   432.4  688.65   461.9  687.65
   491.4  690.28   520.8  692.58   697.7   693.8   786.2  693.16   825.5  691.52
   835.3  692.21     855  696.46   923.8  716.93  1031.9  746.89  1100.6  781.95
  1189.1  818.16  1238.2  846.87  1257.9  856.76  1326.7  879.55  1385.6  890.15
  1395.5  894.39  1434.8  918.08  1464.3  932.45  1483.9  940.86  1513.4  949.34
#Mann= 3 , 0 , 0
       0     .06       0   432.4    .045       0   491.4     .06       0
Bank Sta=432.4,491.4
XS Rating Curve= 0 ,0
Exp/Cntr=0.3,0.1

Type RM Length L Ch R = 1 ,13936.4 ,492.7,495.9,498.5
XS GIS Cut Line= 3
     1842902.024      681249.324     1843568.691      680645.157
     1843768.691      680536.824
#Sta/Elev= 30
       0  799.48    58.7  782.39    97.8   764.8   127.1  759.11   136.9  754.48
   166.2  734.71     176  729.79   205.4  724.09   293.4  696.06   312.9  692.87
   352.1  690.86   420.5  688.68   469.4  689.15     489  686.76   498.8  683.93
   508.5   683.1   528.1  687.14   547.6  690.42     753  692.48   880.1  699.52
   889.9  701.26   918.7  711.66   956.6  722.03     966   726.7   975.5  733.31
   994.5  750.73  1013.4  765.88  1051.3  790.99  1079.8  805.15  1127.2  819.13
#Mann= 3 , 0 , 0
       0     .06       0     489    .045       0   528.1     .06       0
Bank Sta=489,528.1
XS Rating Curve= 0 ,0
Exp/Cntr=0.3,0.1

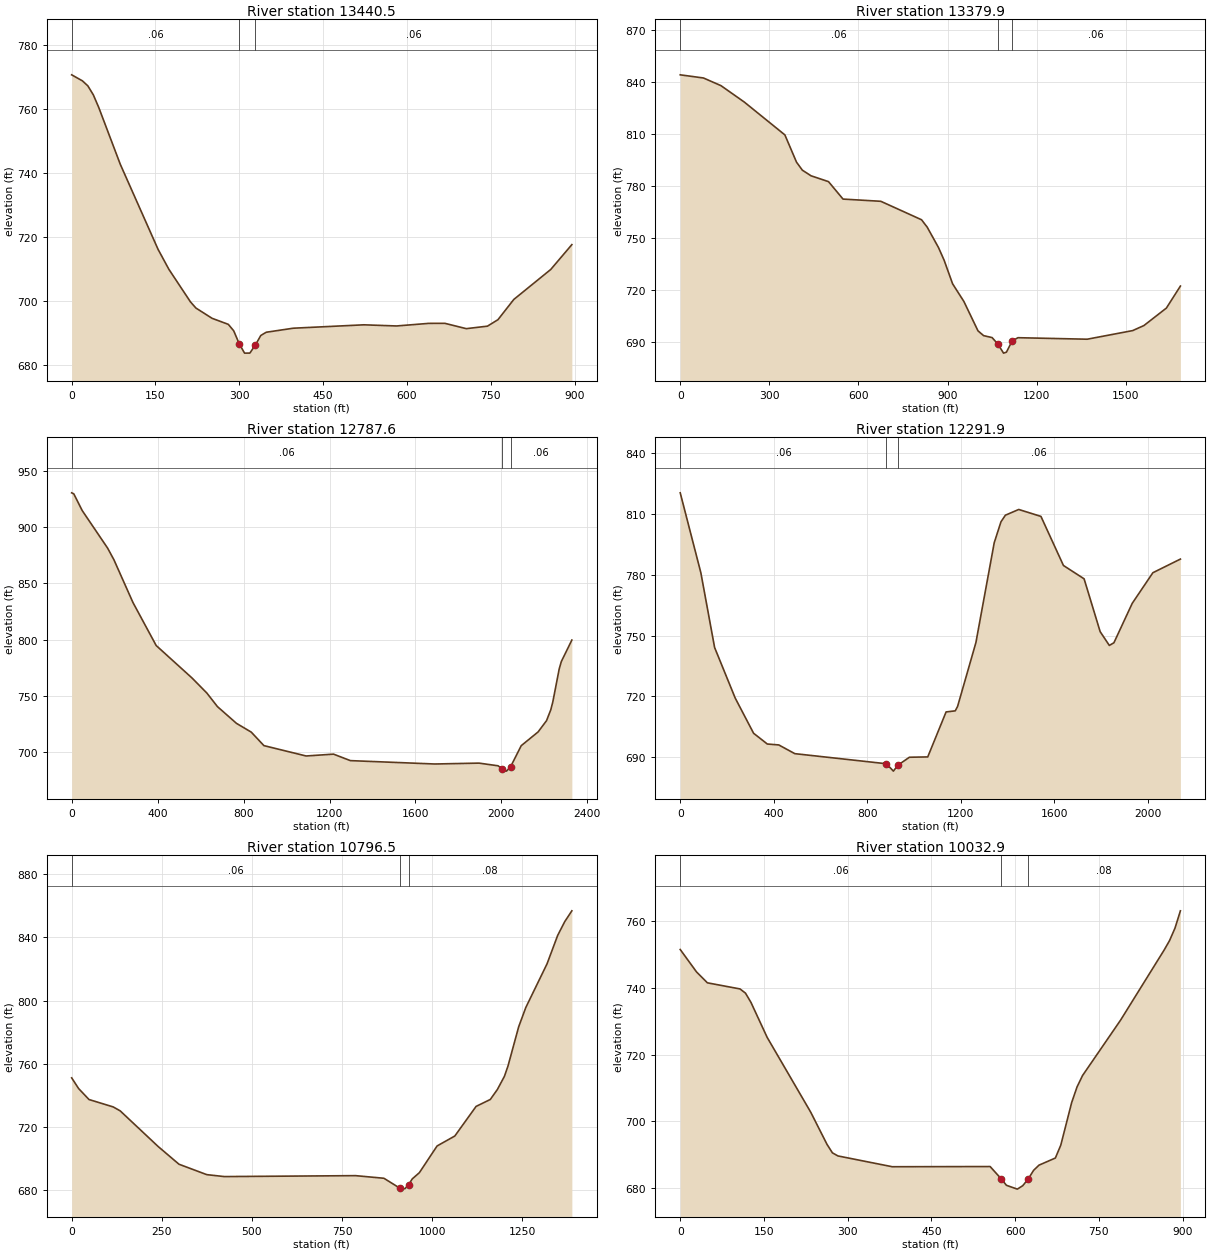
Type RM Length L Ch R = 1 ,13440.5 ,60.6,60.6,60.6
XS GIS Cut Line= 6
     1843116.991      681381.997     1843385.043      681344.768
     1843489.286      681274.032     1843584.221      681126.975
      1843608.42      681004.118     1843781.537      680907.322
#Sta/Elev= 30
       0  770.65    19.3  768.76      29   767.2    38.7  764.41    48.3  760.53
      87  742.72   154.6  716.17     174  709.92   212.6  699.76   222.3  697.84
   251.3  694.62   280.3  692.74     290  690.72   299.7  686.75   309.4  683.75
   318.9  683.76   328.8   686.3   338.5  689.26   348.2  690.27   396.6  691.53
     523  692.59   581.3  692.23   639.1  693.04     668  693.05   706.3  691.39
   744.1  692.17     763   694.2   791.3  700.51   857.4  709.87   895.2  717.63
#Mann= 3 , 0 , 0
       0     .06       0   299.7    .045       0   328.8     .06       0
Bank Sta=299.7,328.8
XS Rating Curve= 0 ,0
Exp/Cntr=0.3,0.1

Type RM Length L Ch R = 1 ,13379.9 ,590,592.3,594.4
XS GIS Cut Line= 6
     1842372.857      681395.157     1843184.975      681421.574
     1843429.719      681387.582     1843533.961      681316.846
     1843653.095      681046.932     1843826.212      680950.136
#Sta/Elev= 30
       0  843.93    78.3  842.11   137.1   837.7   215.4  828.28   352.4  809.31
   391.6  793.59   411.2  788.99   440.5  785.74   499.3  782.37   548.2  772.32
   675.5  771.04   812.6   760.4   831.6  756.15   869.6  744.41   888.6  737.08
   917.1  723.51   955.1  713.32  1002.6  696.39  1021.6  693.62  1050.1   692.5
  1069.3  688.82  1088.7  683.54  1098.4  684.09  1117.8   690.6  1137.2  692.43
  1370.3  691.56  1523.6  696.53  1561.4  699.44    1637  709.51  1684.2  722.18
#Mann= 3 , 0 , 0
       0     .06       0  1069.3    .045       0  1117.8     .06       0
Bank Sta=1069.3,1117.8
XS Rating Curve= 0 ,0
Exp/Cntr=0.3,0.1

Type RM Length L Ch R = 1 ,12787.6 ,521.2,495.7,469.9
XS GIS Cut Line= 3
     1841981.191      682349.324     1842932.579      682196.546
     1844128.665      681540.107
#Sta/Elev= 30
       0  930.48     9.8  929.58    49.2  914.66   167.2  881.34   196.6  870.96
   285.1  832.98   393.3  794.67   560.4  765.74   629.3  752.37   678.4  740.34
   766.9  725.46   835.8  717.65   894.8  705.63  1091.2  696.42  1218.8  698.06
  1297.3  692.29  1689.9  689.29  1896.1  690.07  1984.4   687.7    2004  684.97
  2023.7  682.95  2043.3     687  2092.4   705.6  2170.9  717.81  2210.2  727.86
  2229.8  737.42  2239.6   744.7  2269.1  773.81  2278.9  780.38    2328  799.52
#Mann= 3 , 0 , 0
       0     .06       0    2004    .045       0  2043.3     .06       0
Bank Sta=2004,2043.3
XS Rating Curve= 0 ,0
Exp/Cntr=0.3,0.1

Type RM Length L Ch R = 1 ,12291.9 ,1473.1,1495.3,1516.5
XS GIS Cut Line= 4
     1844226.051      682928.285      1844171.09      681577.228
     1844217.535      681334.679     1844534.347       680898.44
#Sta/Elev= 30
       0  820.51    88.2  781.03     147   744.1   235.2  719.09   313.6  701.75
   372.3  696.42   421.3  695.97   489.9  691.66   881.8  686.67   911.2  683.03
   930.8  685.98   979.8  689.89  1058.2  690.05  1136.6  712.27  1175.8  712.81
  1185.6  714.94    1264  746.48  1342.4  795.87  1371.2   806.2  1390.2  809.46
  1447.2  812.29  1542.1  808.86  1638.3  784.62  1726.6  778.02  1795.2  751.94
  1834.4  745.13    1854  746.43  1932.4  765.92  2020.6  781.04  2138.3  787.78
#Mann= 3 , 0 , 0
       0     .06       0   881.8    .045       0   930.8     .06       0
Bank Sta=881.8,930.8
XS Rating Curve= 0 ,0
Exp/Cntr=0.3,0.1

Type RM Length L Ch R = 1 ,10796.5 ,760.1,763.6,765.2
XS GIS Cut Line= 3
     1844460.105      682839.539     1844699.688      682527.039
     1845477.466      681908.983
#Sta/Elev= 30
       0  751.16    19.2  744.42      48  737.47   115.2  732.79   134.5  730.31
   240.1  707.71   297.7  696.55   374.6  689.98   423.3  688.75   787.2  689.34
   865.9  687.69   909.7   681.5   915.1  680.82   924.7  681.19   934.8  683.71
   944.6   687.3   964.3  691.21  1013.4   708.1  1062.6   714.4  1121.6  733.11
    1161   737.5  1180.7  743.82  1200.3  752.19  1210.2  758.75  1239.7  783.43
  1259.4   795.6  1318.4  823.25  1347.9  841.24  1367.5  849.94  1387.2  856.76
#Mann= 3 , 0 , 0
       0     .06       0   909.7    .045       0   934.8     .08       0
Bank Sta=909.7,934.8
XS Rating Curve= 0 ,0
Exp/Cntr=0.3,0.1

Type RM Length L Ch R = 1 ,10032.9 ,879.3,894.7,911.4
XS GIS Cut Line= 2
     1845022.926      683123.597     1845741.676      682588.441
#Sta/Elev= 30
       0  751.52    29.2   744.8    48.7  741.53   107.1   739.7   116.9  738.44
   126.6  735.71   155.8  725.17   233.8  702.76     263  693.11   272.7  690.57
   282.5  689.65   379.9  686.41   555.2  686.47   574.7  682.86   584.4  680.85
   603.9   679.7   613.6  680.72   623.4  682.73   633.1  685.33   642.8  686.89
   672.1  689.02   681.8  692.88   701.3  705.65     711  710.36   720.8  713.75
     789  730.37   866.9  751.34   876.6  754.17   886.4  757.92   896.1  763.11
#Mann= 3 , 0 , 0
       0     .06       0   574.7    .045       0   623.4     .08       0
Bank Sta=574.7,623.4
XS Rating Curve= 0 ,0
Exp/Cntr=0.3,0.1

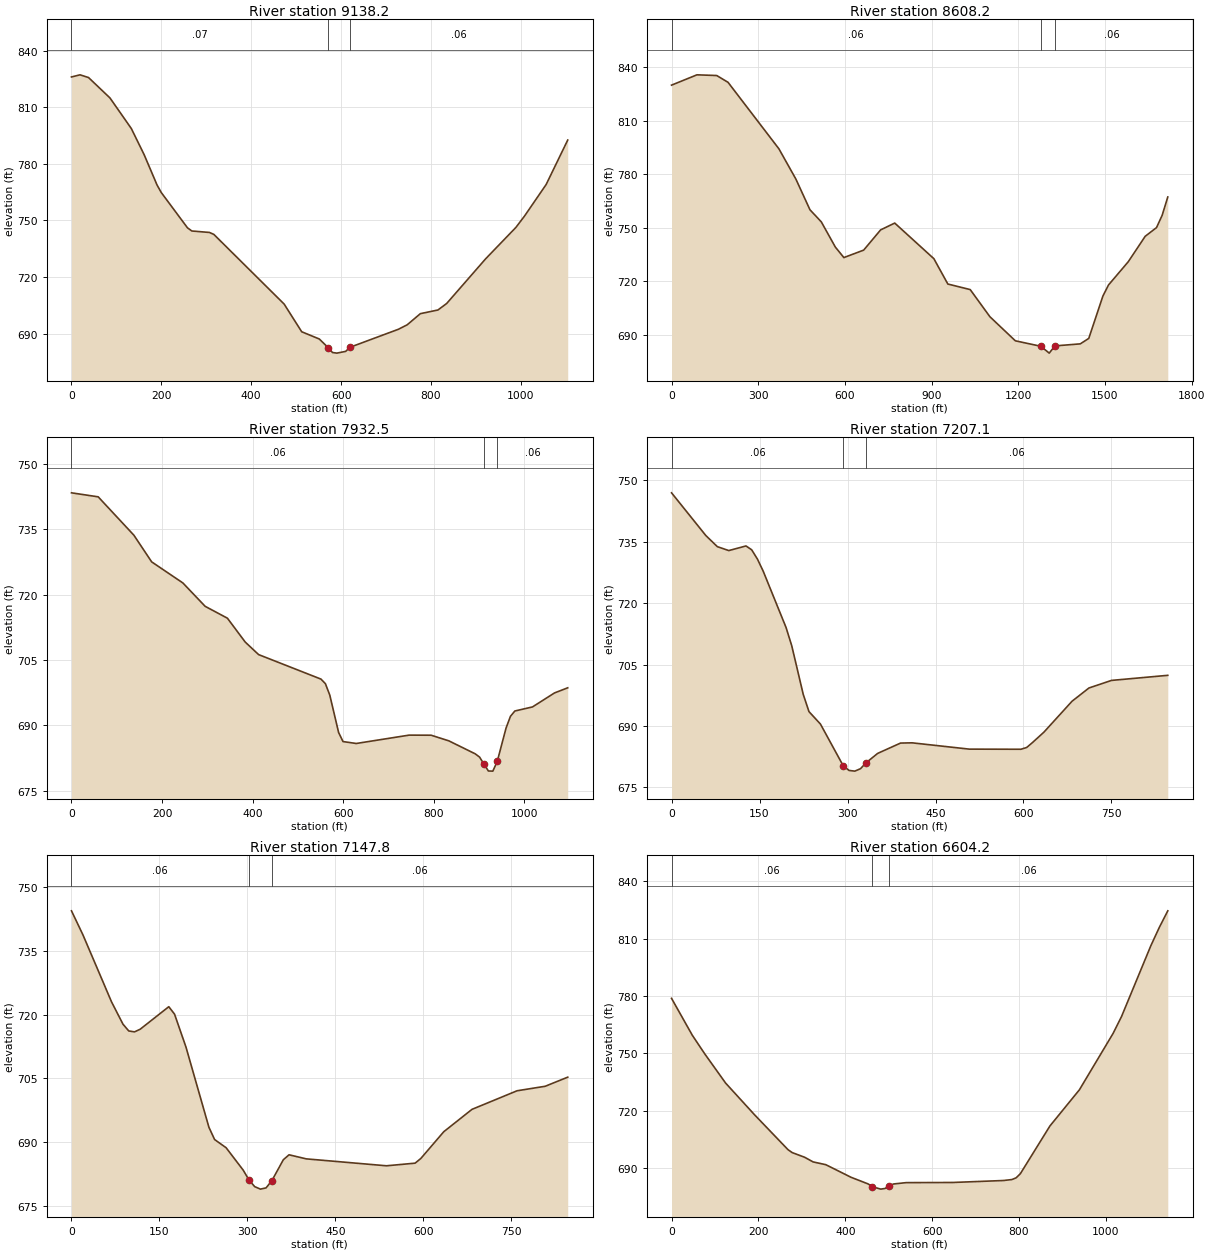
Type RM Length L Ch R = 1 ,9138.2  ,520.6,530,539.4
XS GIS Cut Line= 4
     1845008.716      683443.705     1845168.471        683578.9
      1845796.91      683672.872     1846033.021      683780.511
#Sta/Elev= 30
       0  826.06      19  827.19      38  825.74    85.6  814.95   133.2  798.72
   161.7  784.87   190.3  768.85   199.8  764.81   258.2  746.08   267.9  744.43
     307  743.65   316.8  742.62   473.2   705.7   512.3  691.02   551.4  687.19
     571  682.65   580.8  680.03   590.5   679.7   610.1  680.63   619.9  682.82
   727.4  692.34     747  694.71   776.3  700.62   815.4  702.56   834.9  706.02
   921.6   729.7   988.9  746.33  1008.1  752.36  1056.1  769.03  1104.2  792.62
#Mann= 3 , 0 , 0
       0     .07       0     571    .045       0   619.9     .06       0
Bank Sta=571,619.9
XS Rating Curve= 0 ,0
Exp/Cntr=0.3,0.1

Type RM Length L Ch R = 1 ,8608.2  ,679.7,675.7,671.8
XS GIS Cut Line= 4
      1844265.66      683836.066     1845029.549      683721.483
     1845138.367      683969.539      1845708.68      684328.914
#Sta/Elev= 30
       0  829.93      88  835.71   156.4  835.32   195.6   831.5   371.6  794.27
   430.2  777.36   479.1  760.12   518.2  753.38   567.1  739.18   596.4  733.36
   664.9  737.53   723.6  748.86   772.4  752.68   907.9  732.73   956.2  718.54
  1033.6  715.43  1101.9   700.2  1189.8  686.74  1277.8  683.69  1307.1  679.84
  1326.6  683.88  1414.6  685.03  1443.9  688.08  1492.7  711.76  1512.2     718
  1580.6  731.03  1639.2  745.28  1678.3  750.13  1697.9  757.03  1717.4  767.29
#Mann= 3 , 0 , 0
       0     .06       0  1277.8    .045       0  1326.6     .06       0
Bank Sta=1277.8,1326.6
XS Rating Curve= 0 ,0
Exp/Cntr=0.3,0.1

Type RM Length L Ch R = 1 ,7932.5  ,757.7,725.4,691.3
XS GIS Cut Line= 3
     1844300.383      684843.011     1844713.577      684478.428
     1845223.994        684669.4
#Sta/Elev= 30
       0  743.41      59  742.49   137.8  733.68   177.1  727.55     246  722.71
   295.2  717.34   344.4  714.61   383.8  709.12   413.3  706.25     551  700.62
   560.8  699.57   570.5  696.94     590  688.35   599.7  686.27   628.9  685.83
   745.7  687.75   794.3  687.73   833.3  686.44   891.6  683.46   901.4  682.69
   911.1  681.07   920.8  679.51   930.6  679.48   940.3   681.7   959.8  689.38
   969.5  692.07   979.2  693.29  1018.2  694.23  1066.8  697.44    1096  698.62
#Mann= 3 , 0 , 0
       0     .06       0   911.1    .045       0   940.3     .06       0
Bank Sta=911.1,940.3
XS Rating Curve= 0 ,0
Exp/Cntr=0.3,0.1

Type RM Length L Ch R = 1 ,7207.1  ,59.2,59.2,59.2
XS GIS Cut Line= 4
     1844748.565      685381.377     1844953.147      684949.053
     1845074.738      684850.623     1845277.389      684790.792
#Sta/Elev= 30
       0  746.93    58.6  736.48    78.1  733.79    97.6  732.83   126.9  733.96
   136.6  733.02   146.4  730.76   156.2  727.82   195.2  714.06     205  709.55
   224.5  697.73   234.3  693.51   253.8  690.48   292.8  680.26   302.6  679.15
   312.4  678.98   322.1  679.57   331.9  681.05   351.4  683.31   390.4  685.83
     410  685.89   507.6  684.35   595.6  684.32   605.4  684.75   615.2  685.94
   634.7  688.48   682.8  696.05   711.6  699.28     750  701.13     846  702.37
#Mann= 3 , 0 , 0
       0     .06       0   292.8    .045       0   331.9     .06       0
Bank Sta=292.8,331.9
XS Rating Curve= 0 ,0
Exp/Cntr=0.3,0.1

Type RM Length L Ch R = 1 ,7147.8  ,535.9,543.6,550.7
XS GIS Cut Line= 4
     1844794.886      685421.907     1844999.467      684989.584
     1845121.058      684891.153      1845323.71      684831.323
#Sta/Elev= 30
       0  744.44    19.5   738.8    68.3  723.02    87.8  717.77    97.6  716.18
   107.4  715.96   117.1  716.58   165.9  721.88   175.7  720.13   195.2  712.38
   234.3  693.52     244  690.63   263.6   688.7   292.8  683.42   302.6  681.11
   312.4  679.54   322.1  678.96   331.7  679.25   341.6  680.95   361.2  685.88
   370.9  687.04   400.2  686.08     537  684.45   585.8  685.07   595.6  686.18
   634.7  692.47   682.8  697.73   759.6   702.1   807.6  703.16     846   705.3
#Mann= 3 , 0 , 0
       0     .06       0   302.6    .045       0   341.6     .06       0
Bank Sta=302.6,341.6
XS Rating Curve= 0 ,0
Exp/Cntr=0.3,0.1

Type RM Length L Ch R = 1 ,6604.2  ,1753.3,1756.3,1758
XS GIS Cut Line= 4
     1845105.618       685821.42     1845242.649      685547.358
     1845597.772      685159.425     1845839.023      684964.494
#Sta/Elev= 30
       0   778.8    47.9  759.45    76.6  749.69   124.5  734.44   191.5  717.75
   268.1  699.59   277.7  698.05   306.4  695.61   325.9  693.17   355.1  691.72
   413.5   685.1   452.5  681.65   462.2   680.2   481.7  678.92   491.5  679.27
   501.2  680.58   510.9  681.61   540.2  682.32   647.3   682.4   764.2  683.43
   783.6  683.93   793.4  684.85   803.1  687.01   871.1  711.97     939  730.92
  1016.5  760.42  1035.9  769.24  1103.7  806.47  1123.1     816  1142.5  824.62
#Mann= 3 , 0 , 0
       0     .06       0   462.2    .045       0   501.2     .06       0
Bank Sta=462.2,501.2
XS Rating Curve= 0 ,0
Exp/Cntr=0.3,0.1

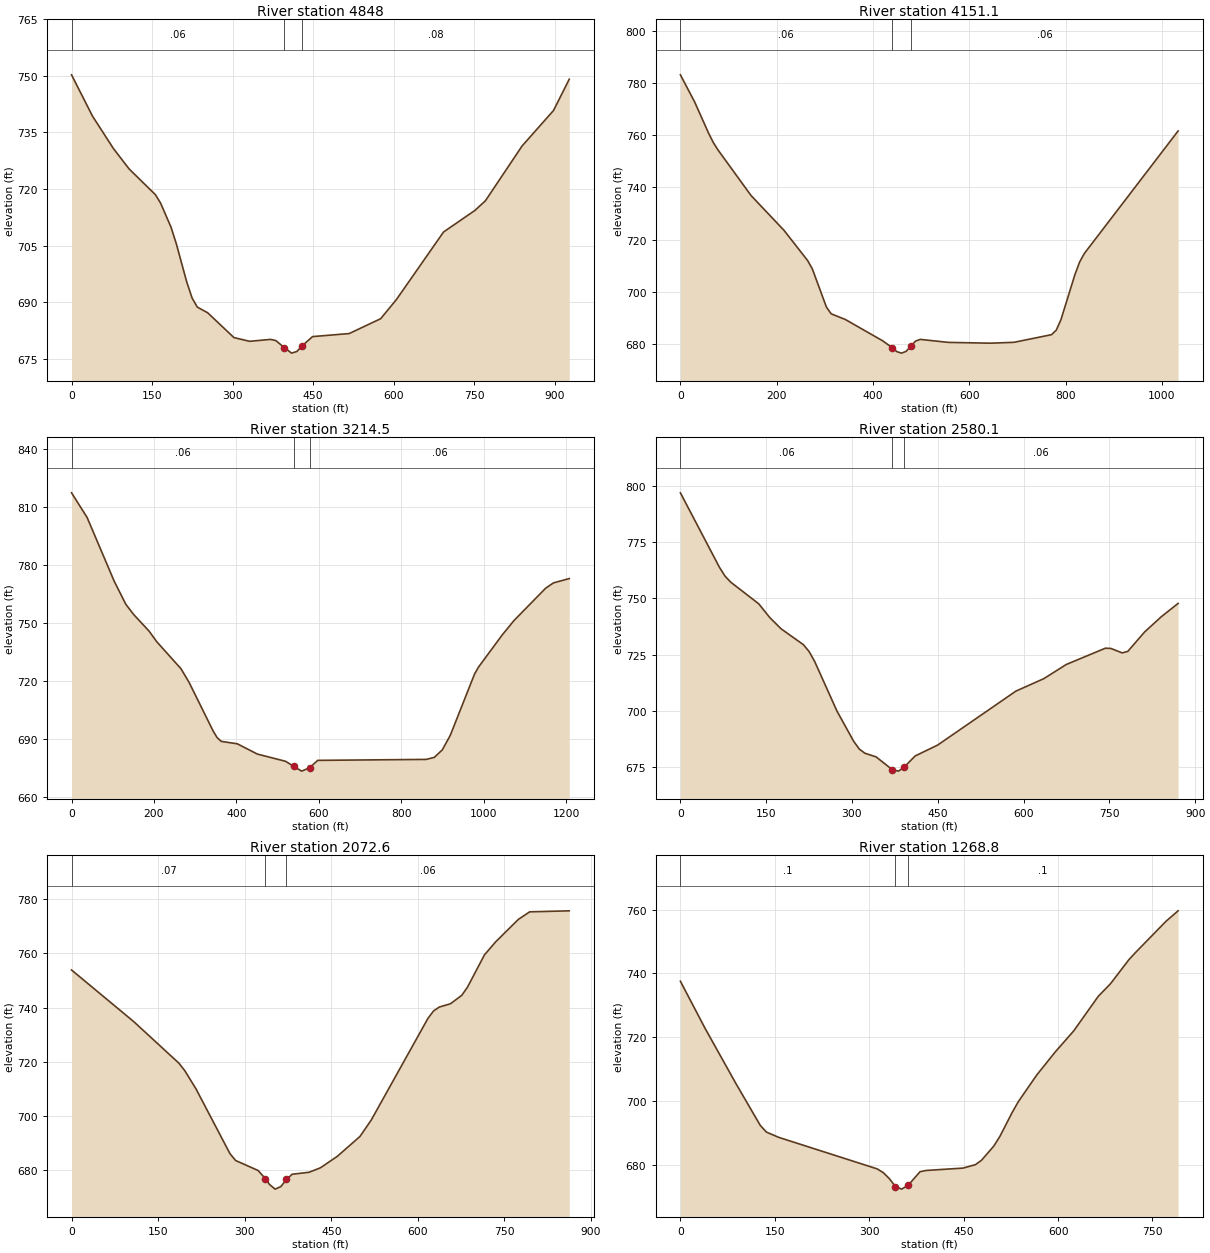
Type RM Length L Ch R = 1 ,4848    ,694.4,696.9,696.2
XS GIS Cut Line= 2
     1845901.833       686912.66     1846655.739      686373.597
#Sta/Elev= 30
       0  750.28      39  739.34      78  730.74   107.3  725.32   156.1  718.53
   165.8  716.29   185.4  709.84   195.1   705.5   214.6  695.34   224.4  691.15
   234.1  688.73   253.6   687.2   302.4  680.64   331.7  679.65   370.7  680.16
   380.5  679.84   396.2  677.98   409.7  676.52   419.5  676.95   429.3  678.44
   448.8   680.9   517.1  681.71   575.6  685.64   604.9  690.71   692.7  708.62
   751.2  714.35   770.7   716.9     839  731.43   897.5  740.83   926.8  749.12
#Mann= 3 , 0 , 0
       0     .06       0   396.2    .045       0   429.3     .08       0
Bank Sta=396.2,429.3
XS Rating Curve= 0 ,0
Exp/Cntr=0.3,0.1

Type RM Length L Ch R = 1 ,4151.1  ,926.8,936.6,945.7
XS GIS Cut Line= 3
     1846202.741      687327.921     1846527.741      687257.087
     1847065.241      686807.087
#Sta/Elev= 30
       0  783.15    29.4  772.82    58.7  760.73    68.5  757.13    78.3  754.29
   146.8  736.85   215.2  723.51   264.2  711.94   273.9  708.77   303.3  694.06
   313.1  691.51   342.4  689.34   420.2  681.14   439.7  678.55   449.5     677
   459.2  676.43   468.9  677.12   478.7  679.18   488.4  681.04   498.1   681.7
   556.6  680.55   644.2  680.24   692.9  680.58   770.8  683.51   780.5  685.23
   790.2  689.19   819.4   706.6   829.2  711.41   838.9  714.64  1033.6  761.62
#Mann= 3 , 0 , 0
       0     .06       0   439.7    .045       0   478.7     .06       0
Bank Sta=439.7,478.7
XS Rating Curve= 0 ,0
Exp/Cntr=0.3,0.1

Type RM Length L Ch R = 1 ,3214.5  ,624.5,634.5,644.3
XS GIS Cut Line= 4
     1846589.333      688049.378      1846737.77      687904.847
     1847507.535      687686.923      1847706.52      687713.441
#Sta/Elev= 30
       0   817.3    37.7  804.58   103.6  771.51   131.8  759.58   150.7  754.32
   188.3  745.68   207.2  740.12   265.7  726.21   285.2   719.2   343.8  693.93
   353.5  690.53   363.3  688.63   402.3  687.37   451.1  682.05   519.4  678.32
   538.9  675.75   558.4  673.23   577.9  674.98   597.4   678.8   860.8   679.3
   880.4  680.35   899.9  684.26   919.4  691.87   977.9  723.42   987.7  727.09
  1045.4  743.78  1074.1  751.26  1150.6  767.92  1169.7  770.69  1207.9  772.91
#Mann= 3 , 0 , 0
       0     .06       0   538.9    .045       0   577.9     .06       0
Bank Sta=538.9,577.9
XS Rating Curve= 0 ,0
Exp/Cntr=0.3,0.1

Type RM Length L Ch R = 1 ,2580.1  ,509,507.5,505.6
XS GIS Cut Line= 2
     1846657.041      688367.087     1847516.416      688503.805
#Sta/Elev= 30
       0  796.95    68.4  763.79    78.2  759.88      88  757.24   136.9  747.64
   156.4  741.48     176  736.53   215.1  729.45   224.9  726.46   234.7  722.04
   273.8  699.93   303.1  686.47   312.9  683.05   322.6  681.21   342.2  679.59
   370.7  673.87   381.3  673.26   391.1  675.02   410.6  680.02   449.8  684.84
   586.6  708.82   635.5  714.37   674.6  720.65   743.1   727.9   752.8  727.78
   772.4  725.81   782.2  726.47   811.5  735.07   840.8  741.88   870.2   747.8
#Mann= 3 , 0 , 0
       0     .06       0   370.7    .045       0   391.1     .06       0
Bank Sta=370.7,391.1
XS Rating Curve= 0 ,0
Exp/Cntr=0.3,0.1

Type RM Length L Ch R = 1 ,2072.6  ,821.2,803.8,786
XS GIS Cut Line= 2
     1846546.364       688881.41     1847405.739      688951.722
#Sta/Elev= 30
       0  753.86   107.8  734.83   186.2  719.48     196  716.82   215.6  710.05
   274.4  686.21   284.2  683.67   323.3  679.97   335.7  676.99   342.9  674.84
   352.7  673.12   362.5  674.04   372.3  676.67   382.1   678.6   411.5  679.33
   431.1  680.97   460.5  685.22   499.7  692.54   519.3  698.62   617.3  735.99
   627.1  738.76   636.9  740.19   656.5  741.43   676.1  744.55   685.9  747.53
   715.3  759.43   734.9  764.27   774.1  772.51   793.7  775.29   862.2  775.66
#Mann= 3 , 0 , 0
       0     .07       0   335.7    .045       0   372.3     .06       0
Bank Sta=335.7,372.3
XS Rating Curve= 0 ,0
Exp/Cntr=0.3,0.1

Type RM Length L Ch R = 1 ,1268.8  ,753.6,753.9,754.1
XS GIS Cut Line= 2
     1846983.864       689818.91     1847593.239      689315.003
#Sta/Elev= 30
       0  737.57      39  722.91    87.9  705.67   126.9  692.47   136.7  690.37
   156.2  688.73   312.4  678.88   322.2  677.71   331.9  675.82   341.7  673.35
   351.4  672.53   361.7  673.71   380.7  677.97   390.5  678.37   449.1  679.11
   468.6  680.18   478.3  681.54   497.9     686   507.6  689.04   527.2  696.55
   536.9   699.9   566.2  708.25   595.5  715.45   624.8  722.02   663.8  732.83
   683.4  736.82   712.6  744.33   722.4  746.42   771.2  756.28   790.7   759.6
#Mann= 3 , 0 , 0
       0      .1       0   341.7    .045       0   361.7      .1       0
Bank Sta=341.7,361.7
XS Rating Curve= 0 ,0
Exp/Cntr=0.3,0.1

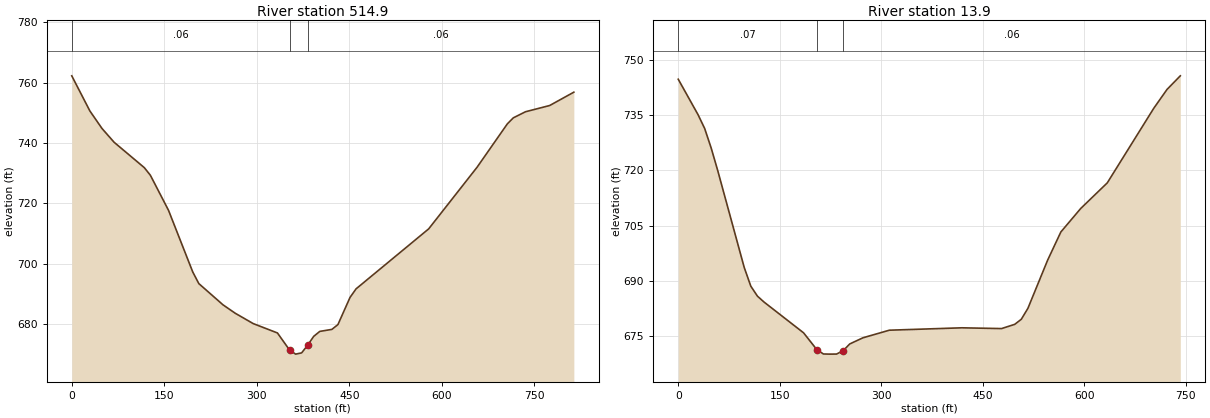
Type RM Length L Ch R = 1 ,514.9   ,499.6,501,501.8
XS GIS Cut Line= 2
     1847401.833      690330.628     1848034.785      689818.639
#Sta/Elev= 30
       0  762.21    29.4  750.58      49   744.8    68.7  740.23   117.7  731.83
   127.5  729.31   156.9  717.72   196.2  697.33     206   693.5   245.2  686.48
   264.8  683.72   294.2  680.27   333.5  677.17   353.1  671.54   362.9  670.17
   372.7  670.58   382.5  673.13   392.3  676.05   402.2  677.69   421.8  678.35
   431.6  679.95   451.2  688.93     461  691.76   578.7  711.59   657.2  731.98
   706.2   746.3     716  748.32   735.6  750.32   774.9  752.39   814.1   756.8
#Mann= 3 , 0 , 0
       0     .06       0   353.1    .045       0   382.5     .06       0
Bank Sta=353.1,382.5
XS Rating Curve= 0 ,0
Exp/Cntr=0.3,0.1

Type RM Length L Ch R = 1 ,13.9    ,14.9,13.9,13
XS GIS Cut Line= 3
      1847766.82      690649.052      1848231.92      690310.675
     1848326.288      690173.167
#Sta/Elev= 30
       0  744.79    29.2  735.18      39  731.43    48.7  726.09    58.5  719.88
    97.5  693.65   107.2  688.58     117  685.86   126.7  684.26   185.2  675.89
   204.7  671.35   214.5  670.14   224.2   670.1     234  670.12   243.7  671.04
   253.5  672.87     273  674.54     312   676.6   419.2  677.25   477.7  677.04
   497.2  678.19   506.9  679.56   516.7  682.54   545.9  695.65   565.4  703.29
   594.8  709.68     634  716.63   702.7   736.9   722.3  742.02   741.9  745.71
#Mann= 3 , 0 , 0
       0     .07       0   204.7    .045       0   243.7     .06       0
Bank Sta=204.7,243.7
XS Rating Curve= 0 ,0
Exp/Cntr=0.3,0.1

Chan Stop Cuts=-1
Use User Specified Reach Order=0
Composite Channel Slope=5